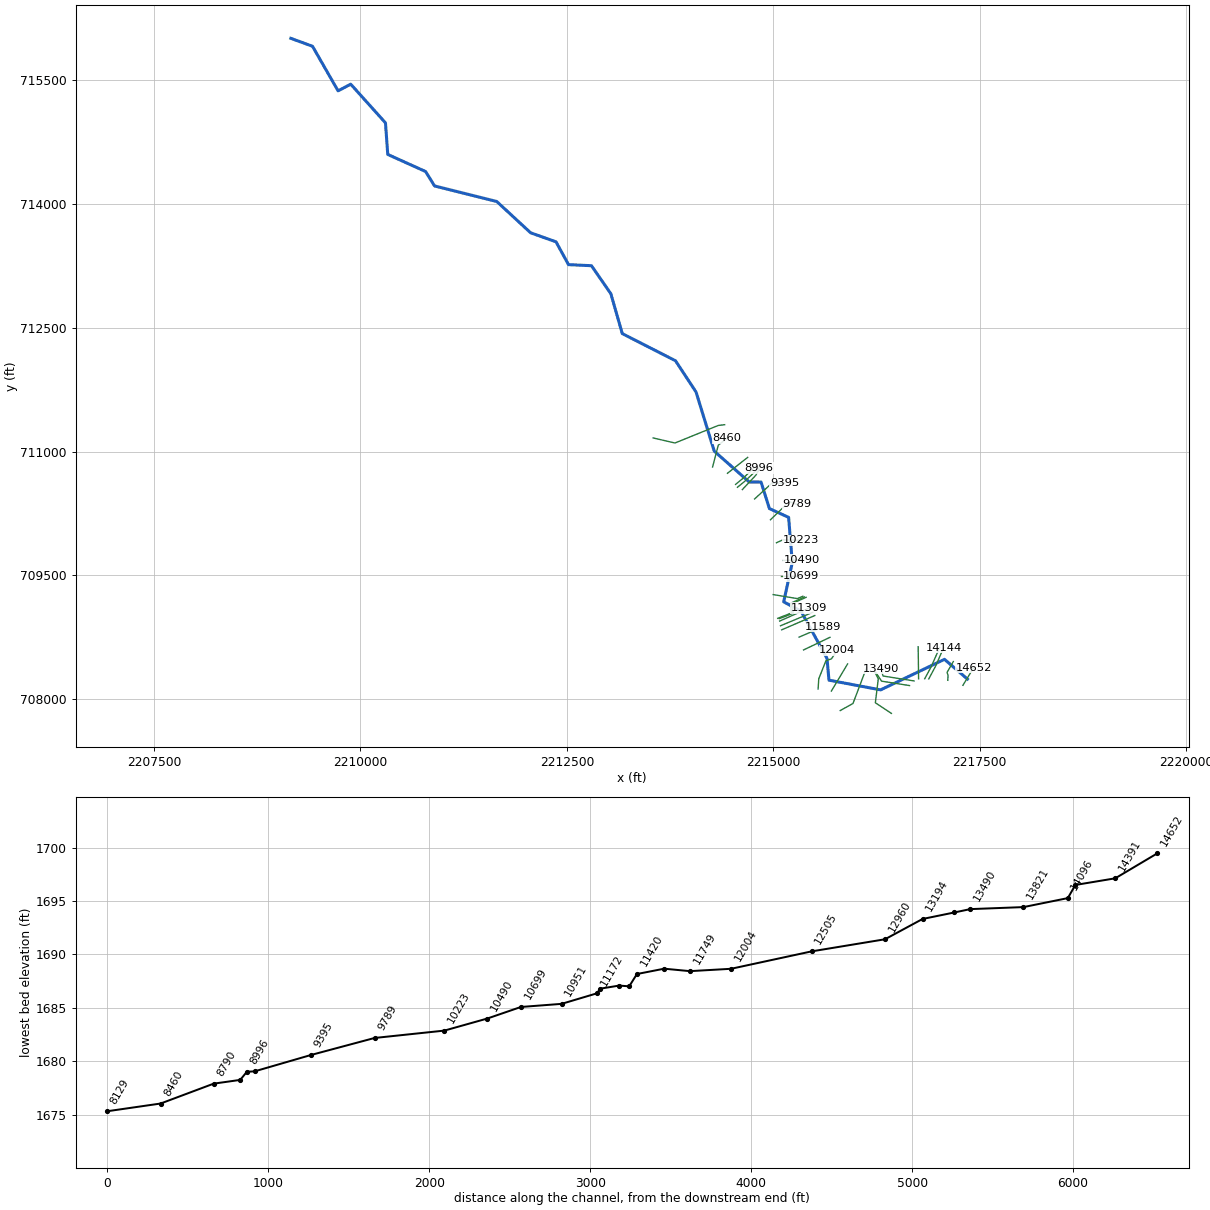
--- LFSANDRN.prj (project) ---

Proj Title=LFSANDRN
Current Plan=p01
Default Exp/Contr=0,0
English Units
Geom File=g01
Flow File=f01
Plan File=p01
BEGIN DESCRIPTION:
---------- MODELED AS PART OF WVEMD CTP PROGRAM, 2023----------
Stream Name: Left Fork Sand Run
Flood Zone:  AFH
Upshur County, WV
HEC-RAS Version: RAS 6.3
Vertical Datum: NAVD88
Projection: NAD 1983 StatePlane West Virginia S FIPS 4702 (US Feet)
Terrain: 1-meter LIDAR (FEMA Region III 3DEP collected 2016-2018)
Land Use: 2019 NLCD
Hydrologic Method:
WV 2010 Regional Regression Equations
Additional Model Notes:
Two lakes on the side
END DESCRIPTION:
DSS Export Rating Curves= 0
DSS Export Rating Curve Sorted= 0
DSS Export Volume Flow Curves= 0
DXF OffsetX= 0
DXF OffsetY= 0
DXF ScaleX= 0
DXF ScaleY= 0

--- LFSANDRN.p01 (plan) ---

Plan Title=Floodplain
Program Version=6.31
Short Identifier=Floodplain
Geom File=g01
Flow File=f01
Subcritical Flow
K Sum by GR= 0
Std Step Tol= 0.01
Critical Tol= 0.01
Num of Std Step Trials= 20
Max Error Tol= 0.3
Flow Tol Ratio= 0.001
Split Flow NTrial= 30
Split Flow Tol= 0.02
Split Flow Ratio= 0.02
Log Output Level= 0
Friction Slope Method= 1
Unsteady Friction Slope Method= 2
Unsteady Bridges Friction Slope Method= 1
Parabolic Critical Depth
Global Vel Dist= 0 , 0 , 0
Global Log Level= 0
CheckData=True
Encroach Param=-1 ,0,0, 0
Mapping Interval=1HOUR
Computation Time Step Use Courant=        0
Computation Time Step Use Time Series=    0
Computation Time Step Count To Double=0
Computation Time Step Max Doubling=0
Computation Time Step Max Halving=0
Computation Time Step Residence Courant=0
Run HTab= 0
Run UNet= 0
Run Sediment= 0
Run PostProcess= 0
Run WQNet= 0
Run RASMapper=-1
UNET Theta= 0
UNET Theta Warmup= 0
UNET ZTol= 0
UNET ZSATol= 0
UNET MxIter= 0
UNET Max Iter WO Improvement= 0
UNET MaxInSteps= 0
UNET DtIC= 0
UNET DtMin= 0
UNET MaxCRTS= 0
UNET WFStab= 0
UNET SFStab= 0
UNET WFX= 1
UNET SFX= 1
UNET Gravity=32.17405
UNET 1D Methodology=Finite Difference
UNET DSS MLevel= 1
UNET Pardiso=0
UNET DZMax Abort= 0
UNET Use Existing IB Tables= 0
UNET Froude Reduction=False
UNET Froude Limit= 0
UNET Froude Power= 0
UNET D1 Cores= 0
UNET WindReference=Eulerian
UNET WindDragFormulation=Hsu (1988)
UNET D2 Coriolis=0
UNET D2 Cores= 0
UNET D2 Theta= 1
UNET D2 Theta Warmup= 1
UNET D2 Z Tol= 0.01
UNET D2 Volume Tol= 0.01
UNET D2 Max Iterations= 20
UNET D2 Equation= 0
UNET D2 RampUpFraction=0.1
UNET D2 TimeSlices= 1
UNET D2 Turbulence Formulation=Non-Conservative (original)
UNET D2 Eddy Viscosity=0.3
UNET D2 Transverse Eddy Viscosity=0.1
UNET D2 Smagorinsky Mixing=0
UNET D2 BCVolumeCheck=0
UNET D2 Cores=0
UNET D2 SolverType=PARDISO (Direct)
UNET D2 Minimum Iterations= 3
UNET D2 Maximum Iterations= 30
UNET D2 Restart Number= 10
UNET D2 Relaxation Coeff=1.3
UNET D2 SOR Precondition Iterations= 10
UNET D2 ILUT Maximum Fill= 8
UNET D2 ILUT Tolerance=1E-08
UNET D2 Convergence Tolerance=0.00001
UNET D1D2 MaxIter= 0
UNET D1D2 ZTol=0.01
UNET D1D2 QTol=0.1
UNET D1D2 MinQTol=1
Write IC File= 0
Write IC File at Fixed DateTime=0
Write IC File at Sim End=0
Echo Input=False
Echo Parameters=False
Echo Output=False
Write Detailed= 0
HDF Write Warmup=0
HDF Write Time Slices=0
HDF Flush=0
HDF Compression= 1
HDF Chunk Size= 1
HDF Spatial Parts= 1
HDF Use Max Rows=0
HDF Fixed Rows= 1
Calibration Method= 0
Calibration Iterations= 20
Calibration Max Change=0.05
Calibration Tolerance=0.2
Calibration Maximum=1.5
Calibration Minimum=0.5
Calibration Optimization Method= 1
WQ AD Non Conservative
WQ ULTIMATE=-1
WQ Max Comp Step=1HOUR
WQ Output Interval=15MIN
WQ Output Selected Increments= 0
WQ Create Restart=0
WQ Fixed Restart=0
WQ System Summary=0
WQ Write To DSS=0
Sorting and Armoring Iterations= 10
XS Update Threshold= 0.02
Bed Roughness Predictor= 0
Hydraulics Update Threshold= 0.02
Energy Slope Method= 1
Volume Change Method= 1
Sediment Retention Method= 0
Sediment TS Multiplier= 1
Warm Up Method= 0
XS Weighting Method= 0
Number of US Weighted Cross Sections= 1
Number of DS Weighted Cross Sections= 1
Upstream XS Weight=0
Main XS Weight=1
Downstream XS Weight=0
Number of DS XS's Weighted with US Boundary= 1
Upstream Boundary Weight= 1
Weight of XSs Associated with US Boundary= 0
Number of US XS's Weighted with DS Boundary= 1
Downstream Boundary Weight= 0.5
Weight of XSs Associated with DS Boundary= 0.5
Percentile Method= 0
Sediment Output Level= 3
Mass or Volume Output= 0
Output Increment Type= 1
Profile and TS Output Increment= 1
Transport Output Increment 1
XS Output Flag= 0
XS Output Increment= 10
Read HDF5 Sediment Hotstart= 0
Sediment Hotstart Type= 0
Write Gradation File= 0
Read Gradation Hotstart= 0
Write HDF5 File= 1
Write Binary Output= 1
Write DSS Sediment File= 0
DSS Sediment Output Type= 1
SV Curve= 0
Specific Gage Flag= 0
Subcell Erosion Methods= 0
Subcell Deposition Methods= 0
Advection Scheme= 1
Matrix Solver= 0
Implicit Weighting Factor= 1
Maximum Outer Loop Convergence Iterations= 5
Convergence Maximum Absolute= 0.001
Convergence RMSE= 0.0001
Grain Fractions Max Abs Error= 0.001
Max Subgrid Regions= 1
Max Subgrid Length Scale= 3.402823E+38
Initial Layer Thickness= 3.402823E+38
Min Layer Thickness= 3.402823E+38
Max Layer Thickness= 3.402823E+38
Number of Layers= 5

--- LFSANDRN.f01 (steady flow) ---

Flow Title=Flows
Program Version=6.31
Number of Profiles= 1
Profile Names=01pct
River Rch & RM=LFSANDRN,Main,14652
     567
River Rch & RM=LFSANDRN,Main,9044
     636
River Rch & RM=LFSANDRN,Main,6788
     736
River Rch & RM=LFSANDRN,Main,2317
     962
Boundary for River Rch & Prof#=LFSANDRN,Main            , 1
Up Type= 0
Dn Type= 3
Dn Slope=0.01752
DSS Import GetInterval= 0
DSS Import GetPeak= 0
DSS Import FillOption= 0

--- LFSANDRN.g01 (geometry) ---

Geom Title=Geometry
Program Version=6.31

River Reach=LFSANDRN        ,Main
Reach XY= 30
2217350.45694596708244.656676069     2217072.531708483.524000019
     2216298.572708113.5429999982215673.67600001708231.184000015
2215650.23900002708493.5680000042215334.31399998709068.327999994
2215125.47199999      709179.3312215229.63500002709656.452000022
2215185.05100004710202.3100000022214952.51400001710308.935000002
2214851.26900001710630.4109999982214708.04400001710630.812000006
2214284.60800001      711003.941     2214064.347711719.951000005
2213815.75700004712098.5750000032213170.71500003712427.834999993
2213032.66900001712910.193000019       2212797.7713249.841000021
     2212520.007 713262.461000012212368.65500003713538.981000006
2212061.51500003713648.0090000182211651.27000003714026.975999996
2210897.83000004714215.4440000062210789.20200005714390.318000019
2210331.28200001714597.0719999972210303.49600001714979.386999995
2209882.83499999 715447.951000022209729.53700003715366.909999996
2209420.16500002715906.8150000132209157.43800001716002.909000009

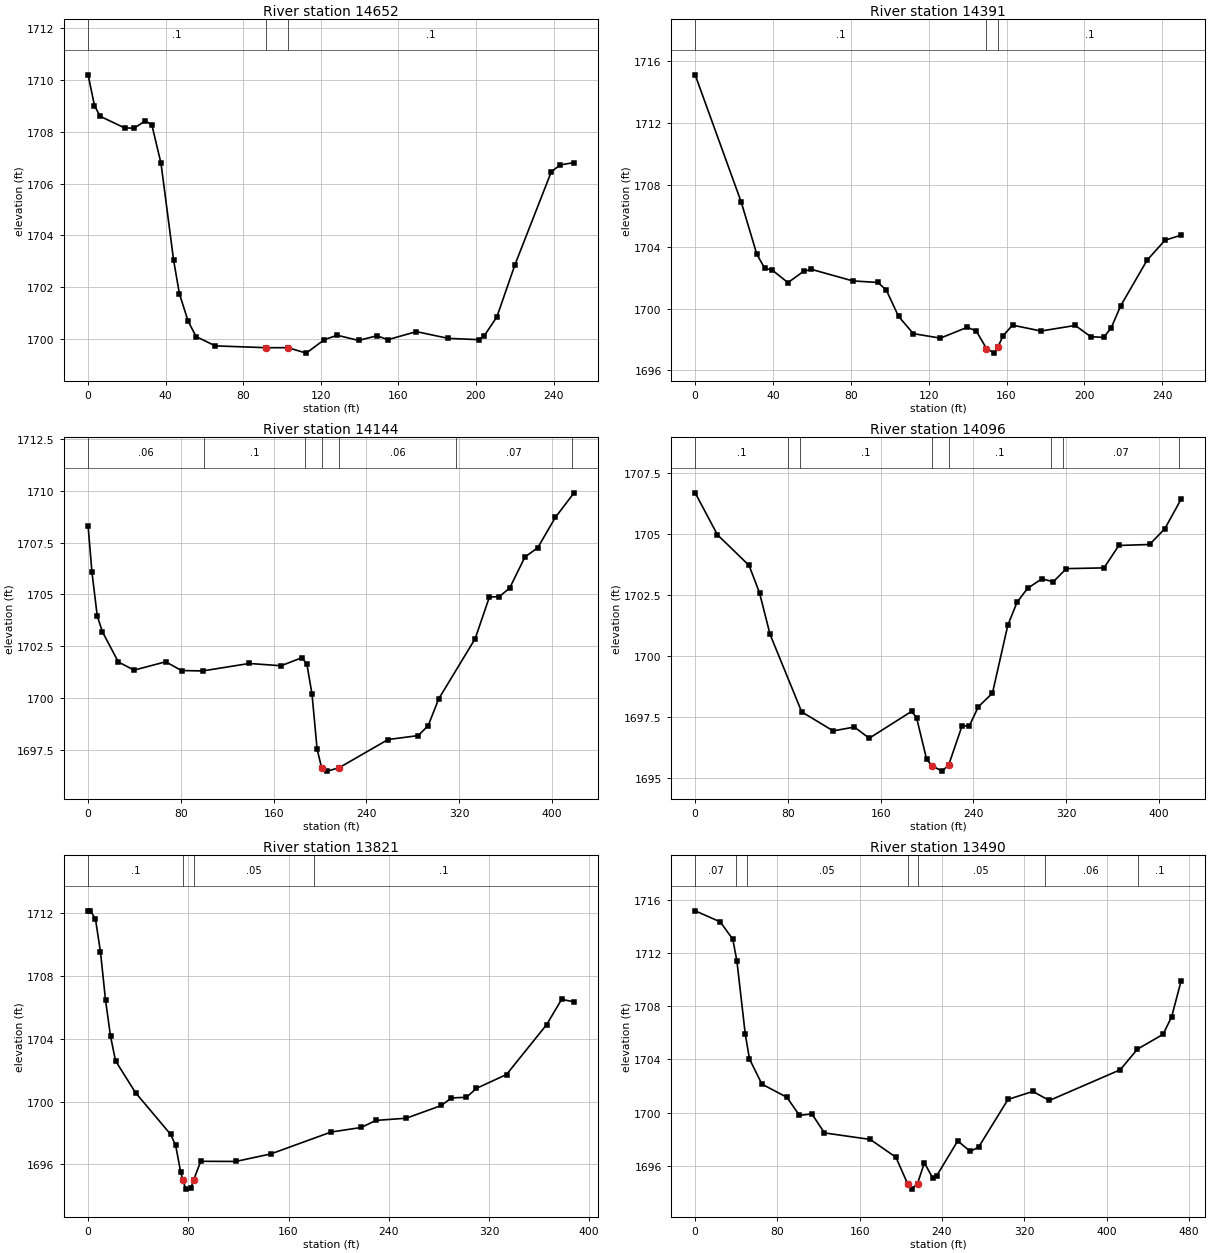
Type RM Length L Ch R = 1 ,14652   ,181.8,260.8,181.8
XS GIS Cut Line= 2
2217295.68253214708169.092217772 2217425.8733549708383.175228682
#Sta/Elev= 30
       0  1710.2     3.3 1709.01     6.2  1708.6    18.8 1708.15    23.7 1708.14
    29.5 1708.42    32.9 1708.26    37.6 1706.78    44.1 1703.04    47.1 1701.74
    51.6 1700.68    55.7 1700.09    65.6 1699.73   91.88 1699.66   103.1 1699.66
   112.5 1699.45   121.8 1699.97   128.5 1700.14   139.5 1699.94   148.9 1700.12
   154.6 1699.97   169.3 1700.28   185.7 1700.02   201.4 1699.97   204.2 1700.11
   210.8 1700.85   220.1 1702.86   238.9 1706.46   243.5 1706.72   250.6 1706.81
#Mann= 3 ,-1,0
       0      .1       0   91.88    .045       0   103.1      .1       0
Bank Sta=91.88,103.1
XS Rating Curve= 0 ,0
Exp/Cntr(USF)=0,0
Exp/Cntr=0.3,0.1

Type RM Length L Ch R = 1 ,14391   ,246.2,247.4,246.2
XS GIS Cut Line= 4
 2217112.2657118708229.5370828472217115.66176862708292.984393384
2217103.18489244 708324.409345692217179.40067444708456.346431279
#Sta/Elev= 30
       0 1715.12    23.7 1706.88    31.7 1703.51    35.7 1702.62    39.7 1702.48
    47.7 1701.68    55.7 1702.41    59.7 1702.54      81 1701.79    93.9 1701.69
    98.2  1701.2   104.5  1699.5   112.1 1698.38     126 1698.09   139.8 1698.79
   144.4 1698.56   149.71697.416   153.7 1697.12   155.51697.502   158.3 1698.26
   163.1 1698.93   177.7 1698.55   195.3 1698.91   203.3 1698.18   209.9 1698.14
   213.7 1698.74   218.7 1700.19   232.2 1703.13   241.4 1704.42   249.7 1704.75
#Mann= 3 ,-1,0
       0      .1       0   149.7    .045       0   155.5      .1       0
Bank Sta=149.7,155.5
XS Rating Curve= 0 ,0
Exp/Cntr(USF)=0,0
Exp/Cntr=0.3,0.1

Type RM Length L Ch R = 1 ,14144   ,47.2,47.2,47.2
XS GIS Cut Line= 3
2216881.80860237708246.2355631822216961.01340157708393.475253996
2217062.55801592 708623.98152858
#Sta/Elev= 30
       0  1708.3     3.3 1706.09     7.9 1703.96    12.4  1703.2    26.1 1701.75
    39.7 1701.36    66.9 1701.76    80.6 1701.34    98.7 1701.32     139 1701.68
   166.4 1701.57   184.5 1701.96   188.7 1701.64   193.1 1700.21   197.5 1697.56
  201.391696.666   206.2  1696.5  216.351696.659   258.7 1698.02   284.7 1698.21
   293.3 1698.69   302.4 1699.98   333.8 1702.87   346.1 1704.88   354.5 1704.89
   363.6 1705.31   376.7  1706.8   387.8 1707.25     403 1708.71   419.1 1709.89
#Mann= 7 ,-1,0
       0     .06       0     100      .1       0  187.19     .06       0
  201.39    .045       0  216.35     .06       0  317.19     .07       0
  417.19      .1       0
Bank Sta=201.39,216.35
XS Rating Curve= 0 ,0
Exp/Cntr(USF)=0,0
Exp/Cntr=0.3,0.1

Type RM Length L Ch R = 1 ,14096   ,275.3,275.3,275.3
XS GIS Cut Line= 3
2216833.06718748708248.2664554692216912.27198668708395.506146283
2217013.81660103708626.012420867
#Sta/Elev= 30
       0 1706.69    19.2 1704.97    46.5 1703.71    55.5 1702.59    64.6 1700.88
    91.9  1697.7   119.1 1696.92   137.3 1697.08   150.1 1696.62   186.6 1697.72
   190.9 1697.47   199.6 1695.76     204  1695.5   212.7 1695.27  218.511695.504
   230.2 1697.13   236.4 1697.12   244.2 1697.91   256.4 1698.47   269.6 1701.25
   277.6  1702.2   286.7 1702.77   298.9 1703.16   308.9 1703.04   320.1 1703.58
   352.6 1703.61   365.4 1704.53   391.9 1704.57   405.1 1705.22   419.1 1706.43
#Mann= 8 ,-1,0
       0      .1       0      80     .06       0      90      .1       0
     204    .045       0  218.51      .1       0  307.19     .06       0
  317.19     .07       0  417.19      .1       0
Bank Sta=204,218.51
XS Rating Curve= 0 ,0
Exp/Cntr(USF)=0,0
Exp/Cntr=0.3,0.1

Type RM Length L Ch R = 1 ,13821   ,339.8,330.7,339.8
XS GIS Cut Line= 2
  2216758.939619708247.2510093252216753.86238829708635.151436159
#Sta/Elev= 30
       0  1712.1     1.9 1712.13     5.9  1711.6     9.9 1709.51    13.9 1706.46
    17.9 1704.16    21.9 1702.59    37.9 1700.56    65.9 1697.91    69.9 1697.21
    73.9 1695.51   75.661695.035    77.9 1694.43    81.9 1694.47    84.3 1695.03
    89.9  1696.2   117.9 1696.19   145.9 1696.67   193.9 1698.06     218 1698.35
   229.7  1698.8   253.9 1698.94     282 1699.75     290 1700.23     302 1700.27
     310 1700.84     334 1701.72     366 1704.89     378  1706.5   387.9 1706.34
#Mann= 4 ,-1,0
       0      .1       0   75.66    .045       0    84.3     .05       0
     180      .1       0
Bank Sta=75.66,84.3
XS Rating Curve= 0 ,0
Exp/Cntr(USF)=0,0
Exp/Cntr=0.3,0.1

Type RM Length L Ch R = 1 ,13490   ,89.6,98,89.6
XS GIS Cut Line= 3
2216704.31948134708222.0125063422216328.70595284708281.416105739
2216303.11671002708370.064554071
#Sta/Elev= 30
       0 1715.18    24.4 1714.35    36.6 1713.04    40.6  1711.4    48.7 1705.92
    52.8 1704.04    64.9 1702.14    89.2 1701.15   101.4 1699.79   113.5  1699.9
   125.7 1698.47   170.2 1697.98   195.2 1696.64  206.511694.655   210.7 1694.24
   216.2 1694.66   222.9 1696.22     231 1695.07     235 1695.26   255.3 1697.87
   267.4 1697.08   275.6  1697.4   304.2 1700.99   328.3 1701.59   344.4 1700.91
   413.3 1703.22     430 1704.77     455 1705.89   463.3 1707.21   472.5 1709.91
#Mann= 7 ,-1,0
       0     .07       0      40     .06       0      50     .05       0
  206.51    .045       0   216.2     .05       0     340     .06       0
  430.28      .1       0
Bank Sta=206.51,216.2
XS Rating Curve= 0 ,0
Exp/Cntr(USF)=0,0
Exp/Cntr=0.3,0.1

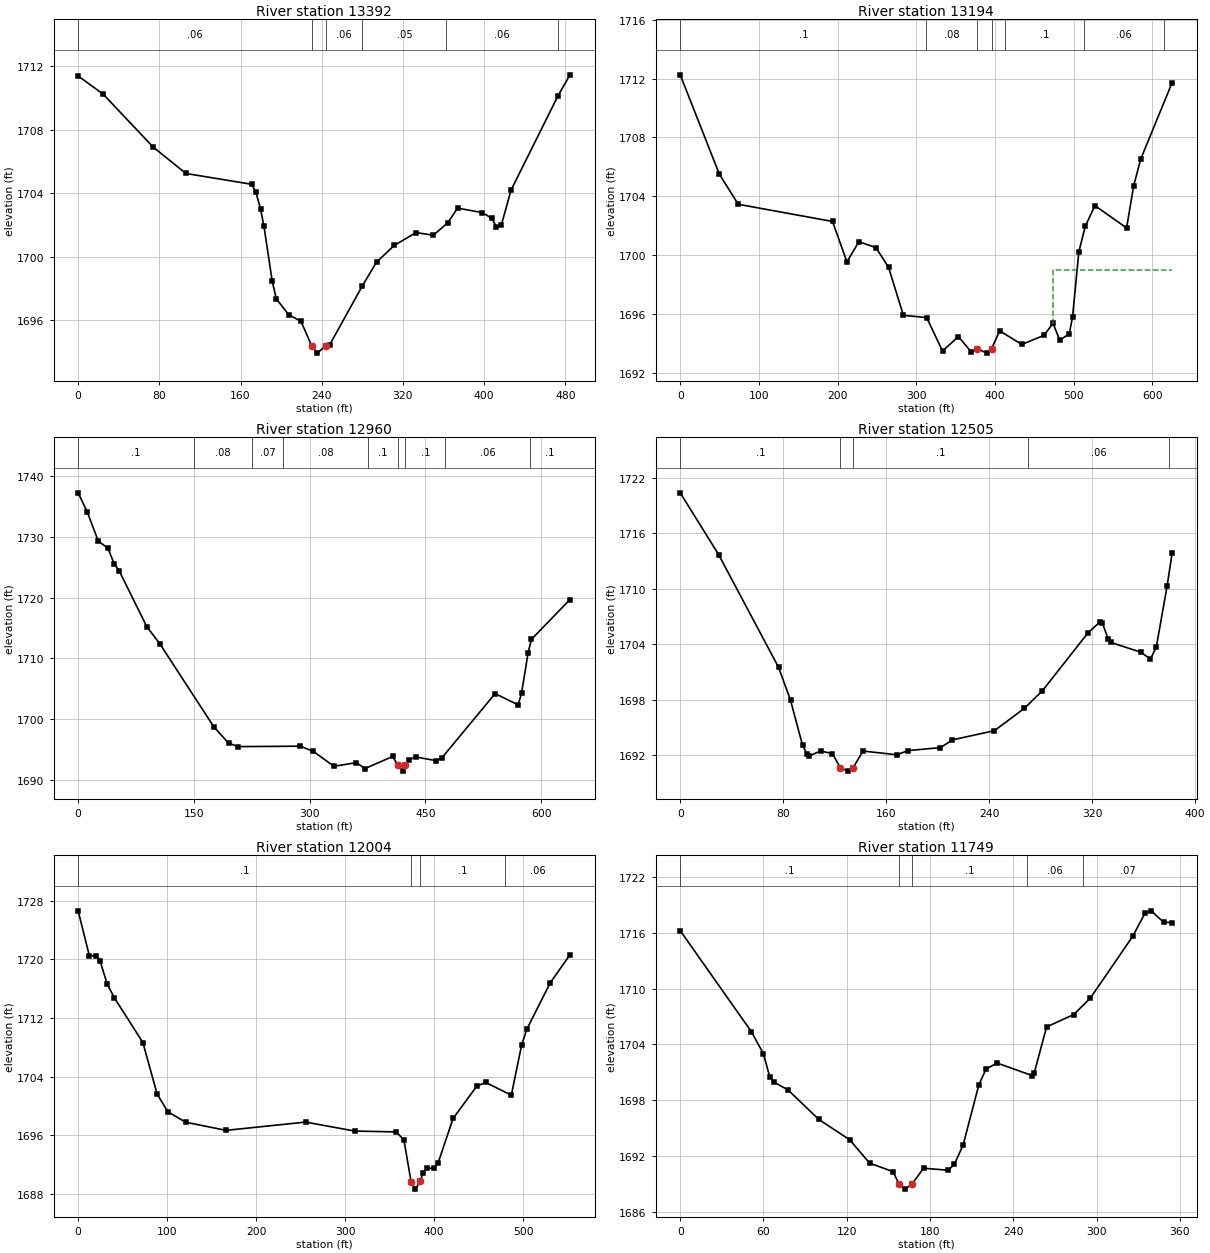
Type RM Length L Ch R = 1 ,13392   ,193.3,198.1,193.3
XS GIS Cut Line= 3
2216649.02843882708165.8075622972216310.42792226708219.270801754
2216232.28934151708337.621049784
#Sta/Elev= 30
       0 1711.38    24.7 1710.23    73.8 1706.91   106.2 1705.24   170.9 1704.56
     175 1704.09   179.7 1703.02   183.1 1701.91   191.2 1698.47   195.2 1697.36
   207.4 1696.35   219.5 1695.94  230.191694.382   235.7 1693.93   243.8 1694.38
   247.9 1694.46     280 1698.16     294 1699.66   311.5 1700.71   332.9 1701.52
   349.9 1701.35   364.3 1702.14   373.8 1703.06     398 1702.78   407.4 1702.43
   412.2 1701.87     417    1702   426.6  1704.2   472.8 1710.13   484.6 1711.45
#Mann= 6 ,-1,0
       0     .06       0  230.19    .045       0   243.8     .06       0
     280     .05       0   362.8     .06       0   472.8      .1       0
Bank Sta=230.19,243.8
XS Rating Curve= 0 ,0
Exp/Cntr(USF)=0,0
Exp/Cntr=0.3,0.1

Type RM Length L Ch R = 1 ,13194   ,209.6,233.8,209.6
XS GIS Cut Line= 4
2216429.75663413707829.131500999 2216235.3562807707957.408035568
2216270.87422984708246.8883400642216225.58091958 708336.78981336
#Sta/Elev= 30
       0 1712.26    49.8 1705.49    73.8 1703.45   193.6 1702.28   211.9 1699.53
   227.1  1700.9   248.8  1700.5   264.9 1699.15   283.7 1695.89   313.3 1695.74
   333.4 1693.46   353.6 1694.45   369.5 1693.43   377.8 1693.61   389.8 1693.32
  395.711693.601     406 1694.84   434.2 1693.91   462.4 1694.53   473.9 1695.35
   482.5 1694.19   494.6 1694.65   498.7 1695.78   506.7 1700.21   514.8 1701.94
   527.1 1703.36   567.4 1701.84   576.4 1704.71   585.4 1706.53   625.2 1711.72
#Mann= 7 ,-1,0
       0      .1       0  312.91     .08       0   377.8    .045       0
  395.71     .08       0  412.91      .1       0  512.91     .06       0
  614.56      .1       0
#XS Ineff= 2 , 0
                          474.14         1699.01
Permanent Ineff=
       F       F
Bank Sta=377.8,395.71
XS Rating Curve= 0 ,0
Exp/Cntr(USF)=0,0
Exp/Cntr=0.3,0.1

Type RM Length L Ch R = 1 ,12960   ,484.3,455.2,484.3
XS GIS Cut Line= 3
2215810.34460827707863.5272654892215964.27137197707948.433926607
2216127.74073268 708379.93918843
#Sta/Elev= 30
       0 1737.28    11.7 1734.17    26.1 1729.32    38.6 1728.16    46.7 1725.58
    53.1 1724.45    88.9 1715.24   105.6 1712.45   175.8 1698.72   194.9 1696.03
   207.3 1695.46   287.8 1695.53   304.9 1694.66   331.4 1692.22   360.5 1692.81
   371.7 1691.85   407.6 1693.84  414.181692.357   420.4 1691.42   424.1 1692.39
     429 1693.33   437.5 1693.75   463.2 1693.16     471 1693.57   540.2 1704.19
   570.1 1702.34   574.4 1704.22   582.9 1710.87   587.2 1713.13   637.2  1719.7
#Mann= 9 ,-1,0
       0      .1       0     150     .08       0  225.79     .07       0
  265.79     .08       0  375.79      .1       0  414.18    .045       0
   424.1      .1       0  475.79     .06       0  585.79      .1       0
Bank Sta=414.18,424.1
XS Rating Curve= 0 ,0
Exp/Cntr(USF)=0,0
Exp/Cntr=0.3,0.1

Type RM Length L Ch R = 1 ,12505   ,510,501.2,495.3
XS GIS Cut Line= 2
2215702.96464457708099.6309803412215898.94575027708427.620084706
#Sta/Elev= 30
       0 1720.37    29.8  1713.7    76.4 1701.51    85.7 1697.95      95  1693.1
    98.3 1692.19    99.7  1691.9     109 1692.47   118.3 1692.18   124.5 1690.63
   130.4 1690.29  134.051690.594     142 1692.46   168.3 1692.06     177 1692.51
   202.2 1692.83   211.5 1693.67   244.1 1694.66   267.3 1697.07   281.4 1698.98
     317 1705.27   325.8 1706.37     328 1706.29   332.6 1704.52   334.5  1704.2
   357.9 1703.14   365.3  1702.4   369.9 1703.73   378.3 1710.33   382.1 1713.82
#Mann= 5 ,-1,0
       0      .1       0   124.5    .045       0  134.05      .1       0
     270     .06       0     380      .1       0
Bank Sta=124.5,134.05
XS Rating Curve= 0 ,0
Exp/Cntr(USF)=0,0
Exp/Cntr=0.3,0.1

Type RM Length L Ch R = 1 ,12004   ,253.1,255.2,255
XS GIS Cut Line= 5
2215542.27326816708124.631967672 2215549.9524901708247.918814102
 2215636.8277605708465.958708432 2215703.6300869708489.776552769
2215773.58304345708591.321167123
#Sta/Elev= 30
       0 1726.64    12.6 1720.52    20.6  1720.5    24.6 1719.81    32.6 1716.66
    40.6 1714.79    72.7 1708.67    88.7 1701.65   100.7 1699.22   120.8 1697.79
   166.2 1696.68   255.5 1697.81   310.9 1696.58   357.4 1696.47     366 1695.36
     3741689.669   378.8 1688.66  384.211689.704   387.3 1690.85   391.5 1691.53
     400 1691.49   404.3 1692.21   421.2 1698.31   447.9 1702.72   457.9 1703.22
   486.6 1701.48   498.1 1708.27   503.9 1710.46   530.4 1716.83   552.5 1720.64
#Mann= 4 ,-1,0
       0      .1       0     374    .045       0  384.21      .1       0
  479.16     .06       0
Bank Sta=374,384.21
XS Rating Curve= 0 ,0
Exp/Cntr(USF)=0,0
Exp/Cntr=0.3,0.1

Type RM Length L Ch R = 1 ,11749   ,160.3,160,159.3
XS GIS Cut Line= 2
 2215366.0219738708597.2297708332215685.69946343708750.173510972
#Sta/Elev= 30
       0 1716.24    51.2 1705.39      60 1702.99    64.5 1700.51    67.6 1699.95
    77.8 1699.09    99.9 1695.93   122.1 1693.75   136.5 1691.23   153.2 1690.33
   157.7 1689.01     162 1688.44     1671688.968   175.3 1690.69   193.1 1690.47
   197.5  1691.1   203.8 1693.17   215.2 1699.67   220.5 1701.39   228.5 1701.99
   253.5 1700.66   255.1 1700.94     264 1705.89   283.5 1707.21   295.5 1708.98
   326.1 1715.64     335 1718.15   339.4 1718.37   348.3 1717.14   354.4 1717.11
#Mann= 5 ,-1,0
       0      .1       0   157.7    .045       0     167      .1       0
     250     .06       0     290     .07       0
Bank Sta=157.7,167
XS Rating Curve= 0 ,0
Exp/Cntr(USF)=0,0
Exp/Cntr=0.3,0.1

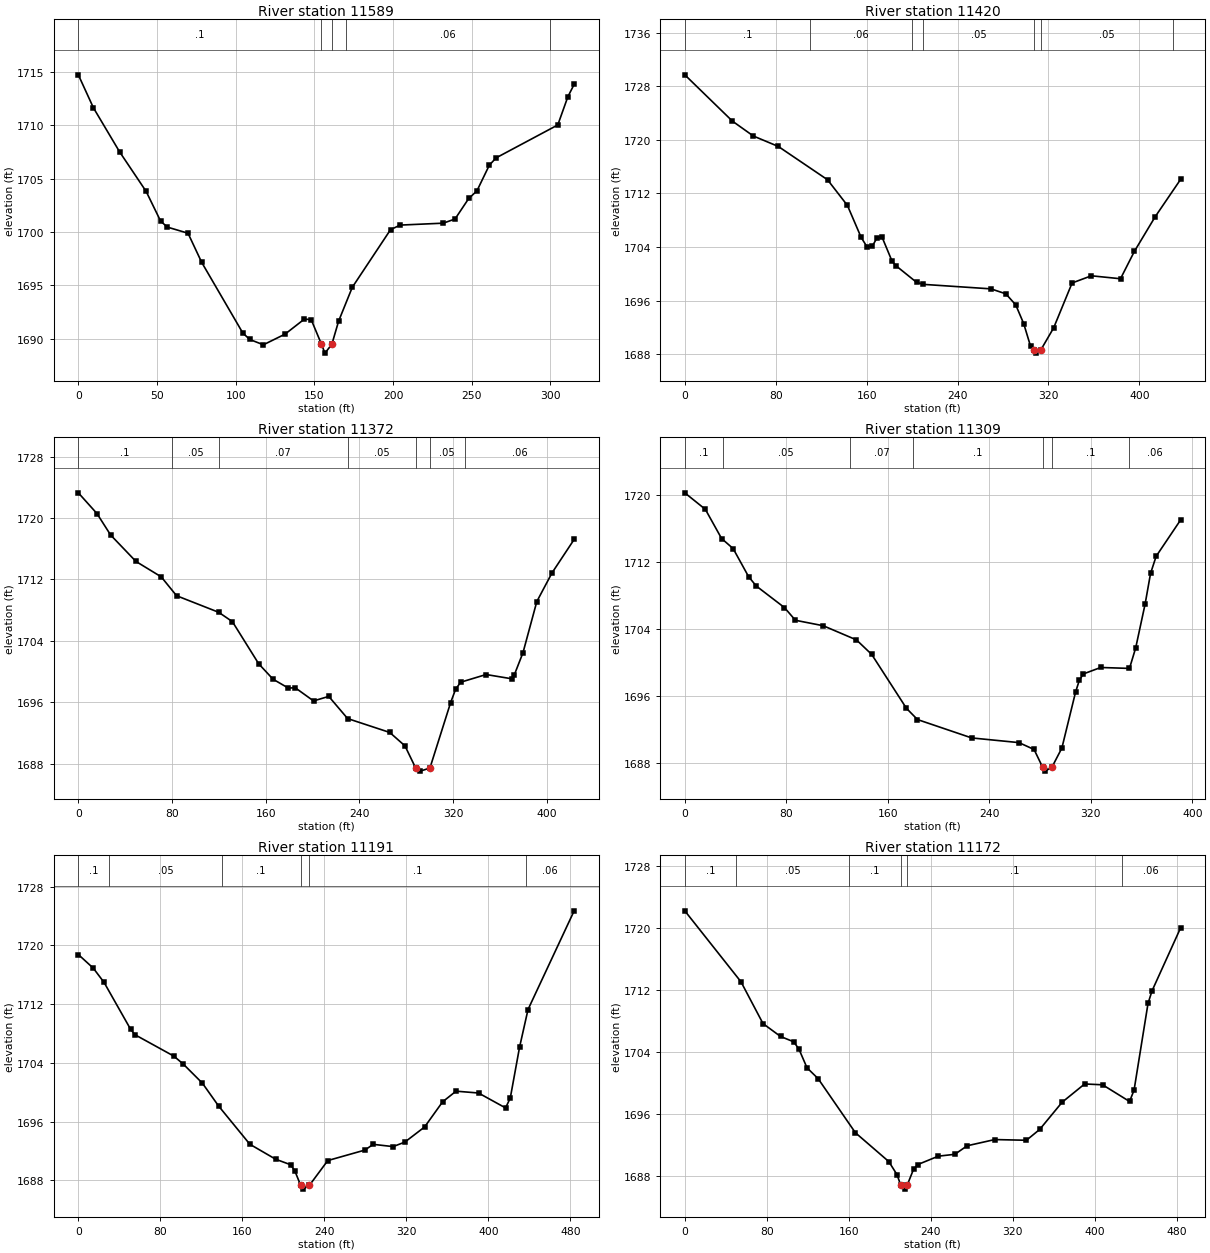
Type RM Length L Ch R = 1 ,11589   ,169,169.3,169
XS GIS Cut Line= 2
2215312.11557359  708752.68078542215601.70577008708876.790869611
#Sta/Elev= 30
       0 1714.71     9.6 1711.62    26.2 1707.51    43.1  1703.8    52.3 1701.02
    56.6 1700.46    69.7 1699.89    78.4 1697.16   104.5 1690.56   108.9 1689.95
   117.6 1689.45   131.4 1690.45   143.7 1691.86     148  1691.8  154.521689.503
   156.7 1688.67   161.1 1689.49   165.4 1691.66   174.1 1694.83   198.4 1700.22
   204.5 1700.65   231.9 1700.83   239.4 1701.22   248.1 1703.14   253.3 1703.85
   261.2 1706.26   265.5 1706.94   304.7 1710.02   311.1 1712.66   315.1 1713.82
#Mann= 5 ,-1,0
       0      .1       0  154.52    .045       0   161.1      .1       0
     170     .06       0     300      .1       0
Bank Sta=154.52,161.1
XS Rating Curve= 0 ,0
Exp/Cntr(USF)=0,0
Exp/Cntr=0.3,0.1

Type RM Length L Ch R = 1 ,11420   ,49.1,47.9,47.6
XS GIS Cut Line= 2
2215100.80805647708840.5746834222215501.41479294709013.437325965
#Sta/Elev= 30
       0  1729.7    41.9 1722.79    60.3 1720.57    82.3 1719.01   125.6 1714.04
   143.1 1710.21   155.2 1705.43   160.5 1703.99   164.9 1704.12   169.2 1705.37
   173.6 1705.47   182.3 1701.92   185.6 1701.24   203.9 1698.74     210 1698.43
   269.4 1697.76   282.5 1697.02   291.2 1695.37   298.2 1692.58   304.3 1689.17
   306.91688.672   308.6 1688.17   313.4 1688.68   324.6 1691.95   340.8 1698.64
   357.8 1699.71   383.4 1699.27   395.6 1703.35   413.9 1708.52   436.3  1714.1
#Mann= 7 ,-1,0
       0      .1       0     110     .06       0     200     .07       0
     210     .05       0   306.9    .045       0   313.4     .05       0
     430     .06       0
Bank Sta=306.9,313.4
XS Rating Curve= 0 ,0
Exp/Cntr(USF)=0,0
Exp/Cntr=0.3,0.1

Type RM Length L Ch R = 1 ,11372   ,63,62.9,63
XS GIS Cut Line= 2
2215086.73946107708889.8147673372215477.59568587709052.926898214
#Sta/Elev= 30
       0 1723.29    15.9 1720.59    27.6 1717.79    49.2 1714.35    70.8 1712.34
    83.9 1709.88   119.9 1707.72   131.6  1706.5   154.1    1701   166.3    1699
   179.3 1697.85   185.3 1697.88   200.9 1696.17   213.9 1696.76     230 1693.87
     266 1692.06     279 1690.31   288.1 1687.43     292 1687.02   300.3 1687.42
     318 1695.96   322.3 1697.71   326.6 1698.61   348.3 1699.61     370 1699.06
   372.2 1699.49   379.8 1702.46   391.6 1709.12   404.6 1712.86   423.5 1717.22
#Mann= 7 ,-1,0
       0      .1       0      80     .05       0     120     .07       0
     230     .05       0   288.1    .045       0   300.3     .05       0
     330     .06       0
Bank Sta=288.1,300.3
XS Rating Curve= 0 ,0
Exp/Cntr(USF)=0,0
Exp/Cntr=0.3,0.1

Type RM Length L Ch R = 1 ,11309   ,106.9,117.6,129.1
XS GIS Cut Line= 2
2215076.42920039 708946.62156868 2215433.7646983 709104.72653323
#Sta/Elev= 30
       0 1720.28    16.2 1718.31      29 1714.83    38.1 1713.63    50.3 1710.28
    56.3 1709.17    78.5  1706.6    87.2 1705.08   109.1 1704.43   135.3 1702.74
   147.3 1701.01   174.7 1694.58   183.4 1693.24   226.1 1691.05   263.4 1690.49
   275.3 1689.67  282.031687.554     284 1687.09  289.351687.555   297.2 1689.84
     308 1696.52     311 1697.94   314.1 1698.68   327.8 1699.45   350.5 1699.34
   355.4  1701.8   362.8 1707.01   367.1 1710.67   371.5 1712.71   390.8 1717.05
#Mann= 7 ,-1,0
       0      .1       0      30     .05       0     130     .07       0
     180      .1       0  282.03    .045       0  289.35      .1       0
     350     .06       0
Bank Sta=282.03,289.35
XS Rating Curve= 0 ,0
Exp/Cntr(USF)=0,0
Exp/Cntr=0.3,0.1

Type RM Length L Ch R = 1 ,11191   ,19.1,19.2,19.2
XS GIS Cut Line= 4
2215072.77359427708975.8664176142215239.10367258709040.753426186
2215226.30905117709157.7328219232215397.20863713709234.500550375
#Sta/Elev= 30
       0 1718.75    14.6 1716.89    25.1 1714.95    50.9 1708.59    55.2 1707.83
    93.2 1704.91   102.5 1703.81     121 1701.23   136.8 1698.12   167.3 1692.91
   192.5 1690.87   207.1 1690.12   211.2 1689.27  216.811687.326   219.2  1686.8
   225.4 1687.32   243.3 1690.69   279.5 1692.12   287.6  1692.9     307 1692.59
   318.4  1693.2   337.7 1695.26   355.3 1698.69   368.4 1700.14   390.3 1699.89
   416.7 1697.86   421.3 1699.21   430.3  1706.1   438.6 1711.26   483.6  1724.7
#Mann= 6 ,-1,0
       0      .1       0      30     .05       0     140      .1       0
  216.81    .045       0   225.4      .1       0  436.22     .06       0
Bank Sta=216.81,225.4
XS Rating Curve= 0 ,0
Exp/Cntr(USF)=0,0
Exp/Cntr=0.3,0.1

Type RM Length L Ch R = 1 ,11172   ,235.9,220.6,205.3
XS GIS Cut Line= 4
2215053.12471139708979.978974495 2215219.4547897709044.865983068
2215206.66016829709161.8453788042215377.55975425709238.613107256
#Sta/Elev= 30
       0 1722.25    54.8  1713.1    76.3 1707.71    93.4 1706.05   106.3 1705.36
   111.4  1704.4   119.2 1702.01     130 1700.62   166.4 1693.64     199 1689.92
     207 1688.23  210.441686.942   215.1 1686.37  217.011686.906   223.1 1688.93
   227.1 1689.53   247.3 1690.62   263.4 1690.86   275.4 1691.96   302.3 1692.76
   333.2 1692.67   346.1 1694.06     368 1697.57     390 1699.93   407.5 1699.82
   433.8 1697.67   438.2 1699.14   451.8 1710.31   455.7 1711.93   483.6 1720.06
#Mann= 6 ,-1,0
       0      .1       0      50     .05       0     160      .1       0
  210.44    .045       0  217.01      .1       0  426.22     .06       0
Bank Sta=210.44,217.01
XS Rating Curve= 0 ,0
Exp/Cntr(USF)=0,0
Exp/Cntr=0.3,0.1

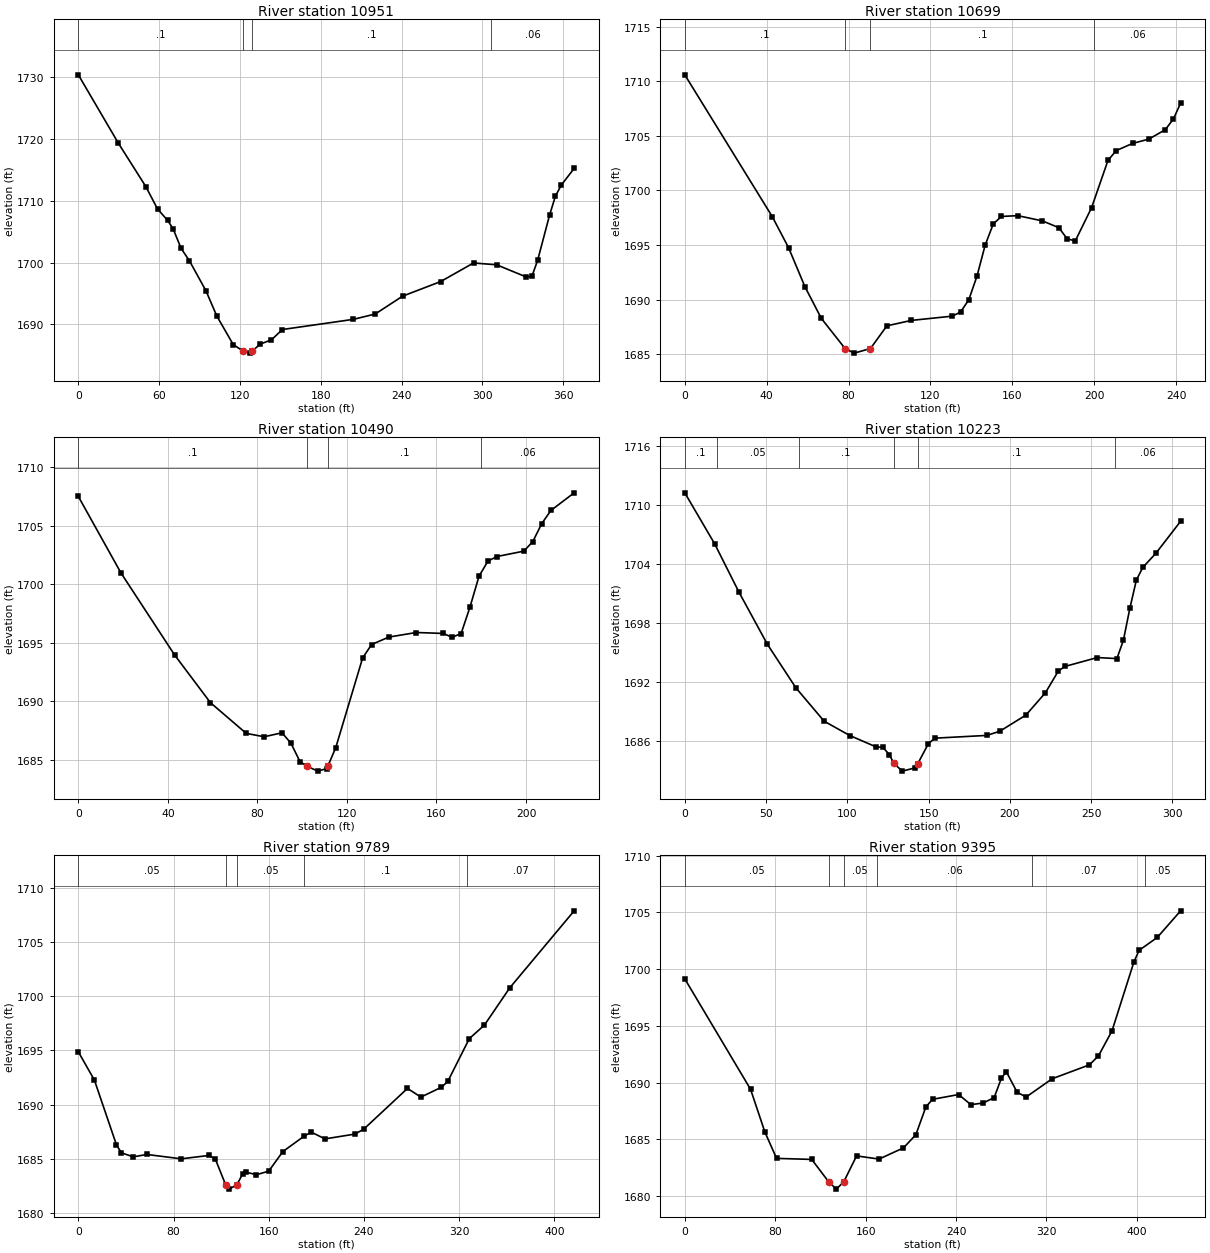
Type RM Length L Ch R = 1 ,10951   ,249.9,252.5,254.3
XS GIS Cut Line= 3
 2214998.7475704709267.4010054262215291.19605975709218.964224379
2215356.99696985709247.295171783
#Sta/Elev= 30
       0 1730.29    29.8 1719.23    50.1 1712.26    58.8 1708.64    66.3  1706.8
    70.4 1705.43    76.2 1702.32    82.5 1700.27    94.7 1695.46   102.8 1691.37
     115 1686.76   122.31685.714   127.1 1685.38  128.991685.704   135.2 1686.85
   143.4 1687.53   151.5 1689.19   204.2 1690.83   220.4 1691.69   240.7 1694.57
     269 1696.93   293.4 1699.93   310.6 1699.63   332.3 1697.69   336.7 1697.76
     341 1700.37   349.8 1707.61   354.1 1710.66   358.5 1712.49   368.1 1715.19
#Mann= 4 ,-1,0
       0      .1       0   122.3    .045       0  128.99      .1       0
  306.43     .06       0
Bank Sta=122.3,128.99
XS Rating Curve= 0 ,0
Exp/Cntr(USF)=0,0
Exp/Cntr=0.3,0.1

Type RM Length L Ch R = 1 ,10699   ,208.8,208.5,208.5
XS GIS Cut Line= 2
2215097.44893556709486.7373724312215339.63284079709486.737372431
#Sta/Elev= 30
       0  1710.6    42.7 1697.61    50.7 1694.75    58.7 1691.17    66.7 1688.27
   78.291685.514    82.7 1685.09    90.7 1685.51    98.7 1687.59   110.7 1688.09
   130.7 1688.48   134.7 1688.86   138.7 1689.97   142.7 1692.13   146.7 1694.98
   150.7 1696.94   154.7 1697.62   162.7 1697.69   174.7 1697.21   182.7 1696.59
   186.7 1695.59   190.7 1695.36   198.7 1698.42   206.7 1702.75   210.7 1703.65
   218.7 1704.31   226.7 1704.71   234.7 1705.57   238.7 1706.56   242.2 1708.01
#Mann= 4 ,-1,0
       0      .1       0   78.29    .045       0    90.7      .1       0
     200     .06       0
Bank Sta=78.29,90.7
XS Rating Curve= 0 ,0
Exp/Cntr(USF)=0,0
Exp/Cntr=0.3,0.1

Type RM Length L Ch R = 1 ,10490   ,268.1,267.1,265.7
XS GIS Cut Line= 2
2215121.23314199709681.0755943052215342.60040128709688.183717309
#Sta/Elev= 30
       0 1707.51      19 1700.98      43 1693.95      59 1689.87      75 1687.24
      83 1686.95      91 1687.29      95 1686.39      99 1684.83  102.131684.427
     107 1684.01     111 1684.23   111.5 1684.45     115 1686.02     127 1693.69
     131 1694.84   138.7 1695.48     151 1695.87     163 1695.79     167 1695.46
     171 1695.78     175 1698.07     179 1700.69     183 1701.98     187 1702.37
     199 1702.83     203 1703.64     207 1705.18   211.1 1706.31   221.5 1707.82
#Mann= 4 ,-1,0
       0      .1       0  102.13    .045       0   111.5      .1       0
     180     .06       0
Bank Sta=102.13,111.5
XS Rating Curve= 0 ,0
Exp/Cntr(USF)=0,0
Exp/Cntr=0.3,0.1

Type RM Length L Ch R = 1 ,10223   ,423.8,433.7,440.3
XS GIS Cut Line= 3
2215037.80283041709895.2669032592215114.97673732 709929.79207214
2215335.32855047709924.714841422
#Sta/Elev= 30
       0 1711.25    18.4 1706.04    33.3 1701.13    50.8 1695.81    68.3 1691.38
    85.7 1687.97   101.5 1686.51   117.8 1685.34   121.8 1685.31   125.8 1684.57
   128.61683.667   133.8 1682.88   141.8 1683.22  143.251683.615   149.8 1685.67
   153.8 1686.24   185.8 1686.52   193.8 1686.95   209.8 1688.59   221.8 1690.86
   229.8 1693.09   233.8 1693.55   253.8 1694.46   265.8 1694.35   269.8 1696.22
   273.8  1699.5   277.8 1702.37   281.8 1703.66   289.7 1705.07     305 1708.35
#Mann= 6 ,-1,0
       0      .1       0      20     .05       0      70      .1       0
   128.6    .045       0  143.25      .1       0  264.54     .06       0
Bank Sta=128.6,143.25
XS Rating Curve= 0 ,0
Exp/Cntr(USF)=0,0
Exp/Cntr=0.3,0.1

Type RM Length L Ch R = 1 ,9789    ,391.5,394.8,392
XS GIS Cut Line= 3
2214965.12783044710173.1607312662215192.63976933710392.934168826
2215287.04948546710358.884763007
#Sta/Elev= 30
       0 1694.87    13.5 1692.26      32 1686.29    36.1 1685.55    46.1 1685.17
    57.6 1685.39    86.4 1684.99   109.9  1685.3   115.2 1684.95   123.8 1682.59
   126.7 1682.19  133.191682.587   138.2 1683.61   140.8 1683.76   149.7 1683.52
     160 1683.85   171.9 1685.66     190  1687.1   195.8 1687.45   207.3 1686.83
   232.3 1687.27   239.8 1687.72   276.6 1691.49   287.9 1690.69   305.2  1691.6
   310.5 1692.14   328.6 1696.09   341.3 1697.34   362.6 1700.78   416.7 1707.89
#Mann= 5 ,-1,0
       0     .05       0   123.8    .045       0  133.19     .05       0
     190      .1       0  326.33     .07       0
Bank Sta=123.8,133.19
XS Rating Curve= 0 ,0
Exp/Cntr(USF)=0,0
Exp/Cntr=0.3,0.1

Type RM Length L Ch R = 1 ,9395    ,357.7,350.3,344.1
XS GIS Cut Line= 3
2214773.21299765710425.4358743812214985.24793388710618.898407445
2215136.92255981710615.803006916
#Sta/Elev= 30
       0 1699.14    58.2  1689.4    70.8 1685.65    81.2 1683.31   112.3 1683.22
  127.26 1681.25     134  1680.6  140.571681.229     152 1683.53   171.9 1683.25
   193.5 1684.24   204.4 1685.39   213.3 1687.85   219.2 1688.52   242.3 1688.94
   253.1 1688.05   263.9 1688.19   273.7 1688.67   280.2  1690.4   284.5 1690.95
     294 1689.15     302 1688.72     325 1690.33     358 1691.56     366 1692.35
     378 1694.56   397.4 1700.64     402 1701.66     418 1702.79   438.7 1705.14
#Mann= 6 ,-1,0
       0     .05       0  127.26    .045       0  140.57     .05       0
     170     .06       0  307.03     .07       0  407.03     .05       0
Bank Sta=127.26,140.57
XS Rating Curve= 0 ,0
Exp/Cntr(USF)=0,0
Exp/Cntr=0.3,0.1

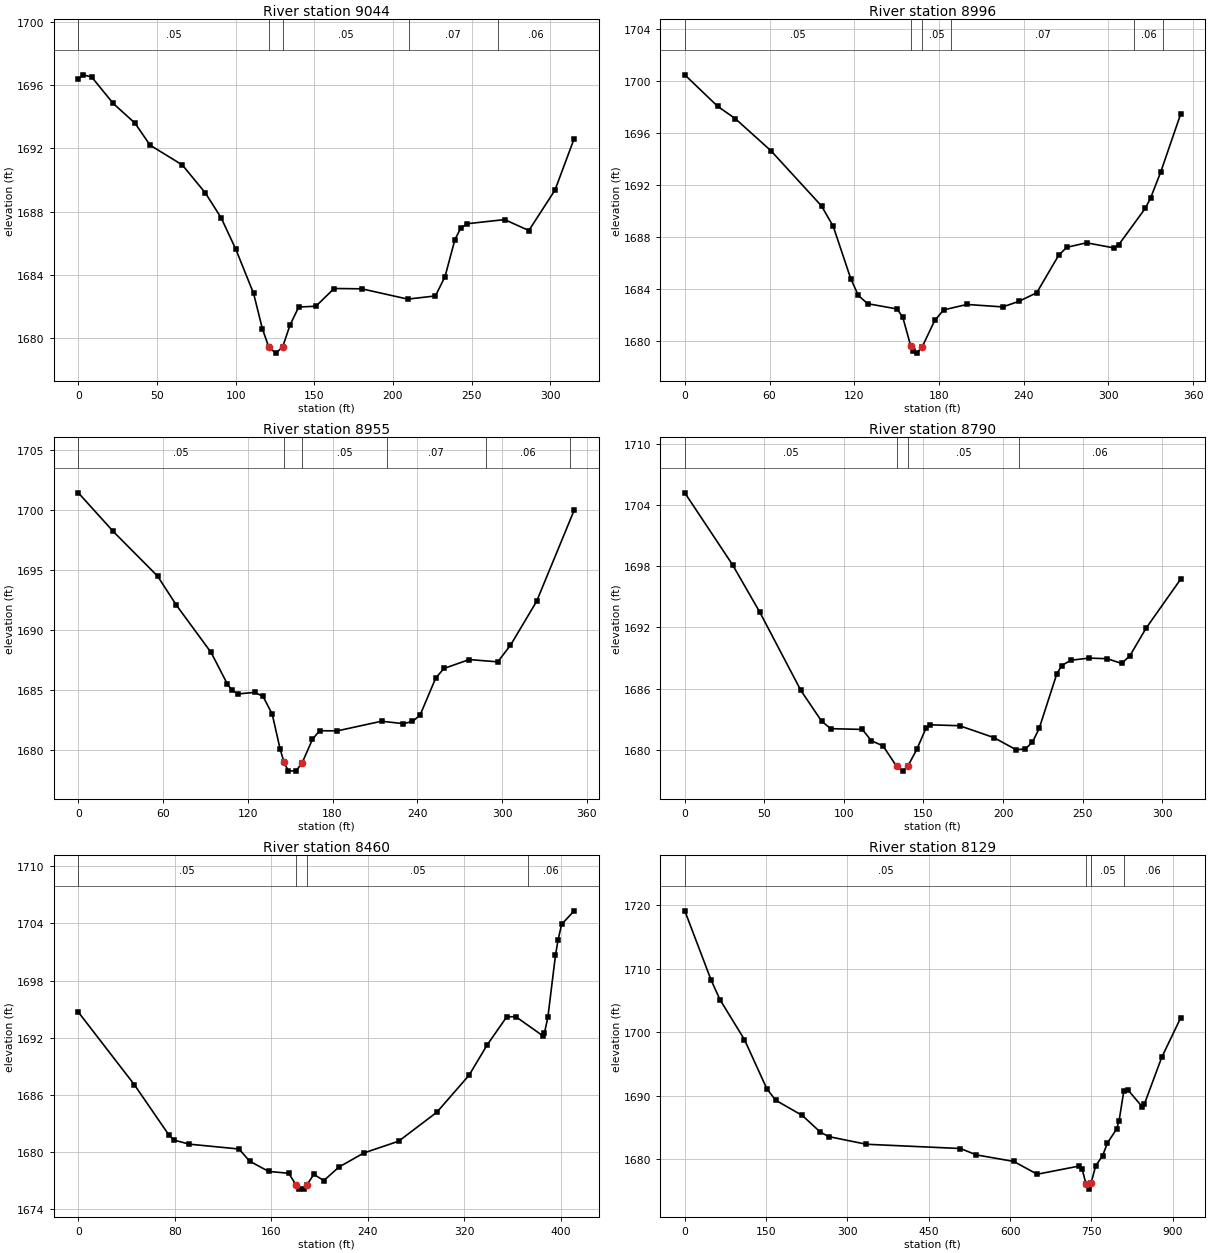
Type RM Length L Ch R = 1 ,9044    ,48.3,48,47
XS GIS Cut Line= 3
2214624.97544483710538.9432272432214786.73384829710711.598111142
2214826.94230924710779.185338646
#Sta/Elev= 30
       0 1696.38     3.1 1696.64     8.5  1696.5    22.2 1694.83      36 1693.59
    45.6  1692.2    66.1 1690.95    80.7 1689.19    90.8 1687.61   100.1 1685.63
   111.4 1682.84     117 1680.61   121.1 1679.44   125.5 1679.07  129.861679.455
   134.6 1680.85   140.1 1681.98     151 1682.03   162.6 1683.15   180.2 1683.13
   209.4 1682.48     227 1682.68   233.1  1683.9   239.4 1686.24   243.1 1686.96
   247.2 1687.24     271  1687.5   286.4 1686.81     303 1689.36   315.2 1692.61
#Mann= 5 ,-1,0
       0     .05       0   121.1    .045       0  129.86     .05       0
     210     .07       0  266.59     .06       0
Bank Sta=121.1,129.86
XS Rating Curve= 0 ,0
Exp/Cntr(USF)=0,0
Exp/Cntr=0.3,0.1

Type RM Length L Ch R = 1 ,8996    ,41.9,41.5,41.3
XS GIS Cut Line= 3
2214565.41674812710566.4460716312214656.80690104710641.589086253
2214826.38640701 710801.01413079
#Sta/Elev= 30
       0 1700.47    23.2 1698.05    35.8 1697.09      61 1694.62    96.8 1690.37
   105.1  1688.8   117.5 1684.77   122.9 1683.47   129.4 1682.84   150.4 1682.43
   154.4 1681.78     160 1679.57   161.4 1679.21   164.4 1679.03  168.211679.539
     177 1681.55   183.3 1682.36   199.8 1682.78   225.1 1682.59   236.4 1683.01
   249.2 1683.68   264.7 1686.56   270.4 1687.18   284.5 1687.53   304.1 1687.13
   307.2 1687.37   326.1 1690.19   329.8 1690.97   337.1 1693.01   351.1 1697.44
#Mann= 6 ,-1,0
       0     .05       0     160    .045       0  168.21     .05       0
  188.32     .07       0  318.32     .06       0  338.32     .05       0
Bank Sta=160,168.21
XS Rating Curve= 0 ,0
Exp/Cntr(USF)=0,0
Exp/Cntr=0.3,0.1

Type RM Length L Ch R = 1 ,8955    ,165.3,164.7,163.2
XS GIS Cut Line= 3
2214542.56920989710601.4789635832214633.95936281710676.621978205
2214803.53886878710836.047022742
#Sta/Elev= 30
       0 1701.42    24.7 1698.21    56.2 1694.48    69.4 1692.08      94 1688.14
   105.6  1685.5   108.9 1684.98   112.9 1684.69     125 1684.82   130.8 1684.48
   137.3 1683.01   142.9  1680.1   145.7 1678.99   148.8 1678.27   154.3 1678.31
  158.541678.972   165.8 1680.92   170.8 1681.63   183.4 1681.62   214.7 1682.42
   230.1 1682.22   236.6  1682.4     242 1682.93   253.1 1686.02   258.9 1686.81
   276.8 1687.55     297 1687.36     306 1688.74   324.5 1692.39   351.1 1699.97
#Mann= 6 ,-1,0
       0     .05       0   145.7    .045       0  158.54     .05       0
  218.32     .07       0  288.32     .06       0  348.32     .05       0
Bank Sta=145.7,158.54
XS Rating Curve= 0 ,0
Exp/Cntr(USF)=0,0
Exp/Cntr=0.3,0.1

Type RM Length L Ch R = 1 ,8790    ,324.7,330,334.9
XS GIS Cut Line= 2
2214444.57865704710736.0255776032214689.30117763710928.960344877
#Sta/Elev= 30
       0  1705.2      30 1698.15    47.1 1693.51    72.9 1685.84      86 1682.81
    91.7 1682.08   111.5 1682.01   117.3  1680.9   124.6 1680.39  133.131678.385
   137.2 1677.92   140.1 1678.39   145.8 1680.05   151.5  1682.1   154.3 1682.46
   172.7 1682.37   194.2 1681.21   208.3 1680.01   214.1 1680.11   218.5 1680.77
   222.7  1682.1   233.8 1687.46   236.9 1688.27   242.6 1688.79     254    1689
   265.4 1688.94   274.5 1688.48   279.7 1689.22   289.8 1691.91   311.6 1696.73
#Mann= 4 ,-1,0
       0     .05       0  133.13    .045       0   140.1     .05       0
     210     .06       0
Bank Sta=133.13,140.1
XS Rating Curve= 0 ,0
Exp/Cntr(USF)=0,0
Exp/Cntr=0.3,0.1

Type RM Length L Ch R = 1 ,8460    ,338.3,331,320.7
XS GIS Cut Line= 3
2214264.33734011710812.2815205562214333.12401853711075.963787844
 2214440.1255183711163.857876939
#Sta/Elev= 30
       0 1694.68    46.4 1687.05    75.3 1681.71    79.3 1681.22    91.9 1680.79
   133.2 1680.28     142    1679   157.8 1677.92   174.4 1677.73  180.471676.499
   182.8 1676.09     187 1676.06   189.5 1676.51   195.2 1677.61   203.5 1676.96
   215.9 1678.37   236.6 1679.86   265.5  1681.1   297.2 1684.15   323.9 1688.04
   338.6 1691.17   355.1 1694.18   362.6  1694.2   385.2 1692.17   386.4  1692.5
   389.2 1694.13   395.5 1700.65   397.7 1702.29   400.6 1703.91     411 1705.33
#Mann= 4 ,-1,0
       0     .05       0  180.47    .045       0   189.5     .05       0
  372.51     .06       0
Bank Sta=180.47,189.5
XS Rating Curve= 0 ,0
Exp/Cntr(USF)=0,0
Exp/Cntr=0.3,0.1

Type RM Length L Ch R = 1 ,8129    ,554.5,555.9,555.3
XS GIS Cut Line= 4
2213545.01173752711164.1567545852213808.69400481711103.013040432
2214332.23705725711315.1052989022214410.57744101711324.659004238
#Sta/Elev= 30
       0 1719.07    48.4 1708.22    64.8 1705.12     110 1698.84   151.1 1691.15
   167.5 1689.31   216.8 1686.91   249.6 1684.33   265.1  1683.6   334.9 1682.39
   508.4 1681.72   537.7 1680.72   606.8 1679.69   649.9 1677.68   727.6 1678.97
   732.7 1678.57  739.711676.214   744.9 1675.34   749.2 1676.23   757.8 1678.99
   770.7 1680.61   779.4 1682.57   796.6 1684.81     801 1686.09   809.6 1690.69
   818.2 1690.84   843.5  1688.3   847.6 1688.69   879.8 1696.08   914.5 1702.23
#Mann= 4 ,-1,0
       0     .05       0  739.71    .045       0   749.2     .05       0
  810.68     .06       0
Bank Sta=739.71,749.2
XS Rating Curve= 0 ,0
Exp/Cntr(USF)=0,0
Exp/Cntr=0.3,0.1