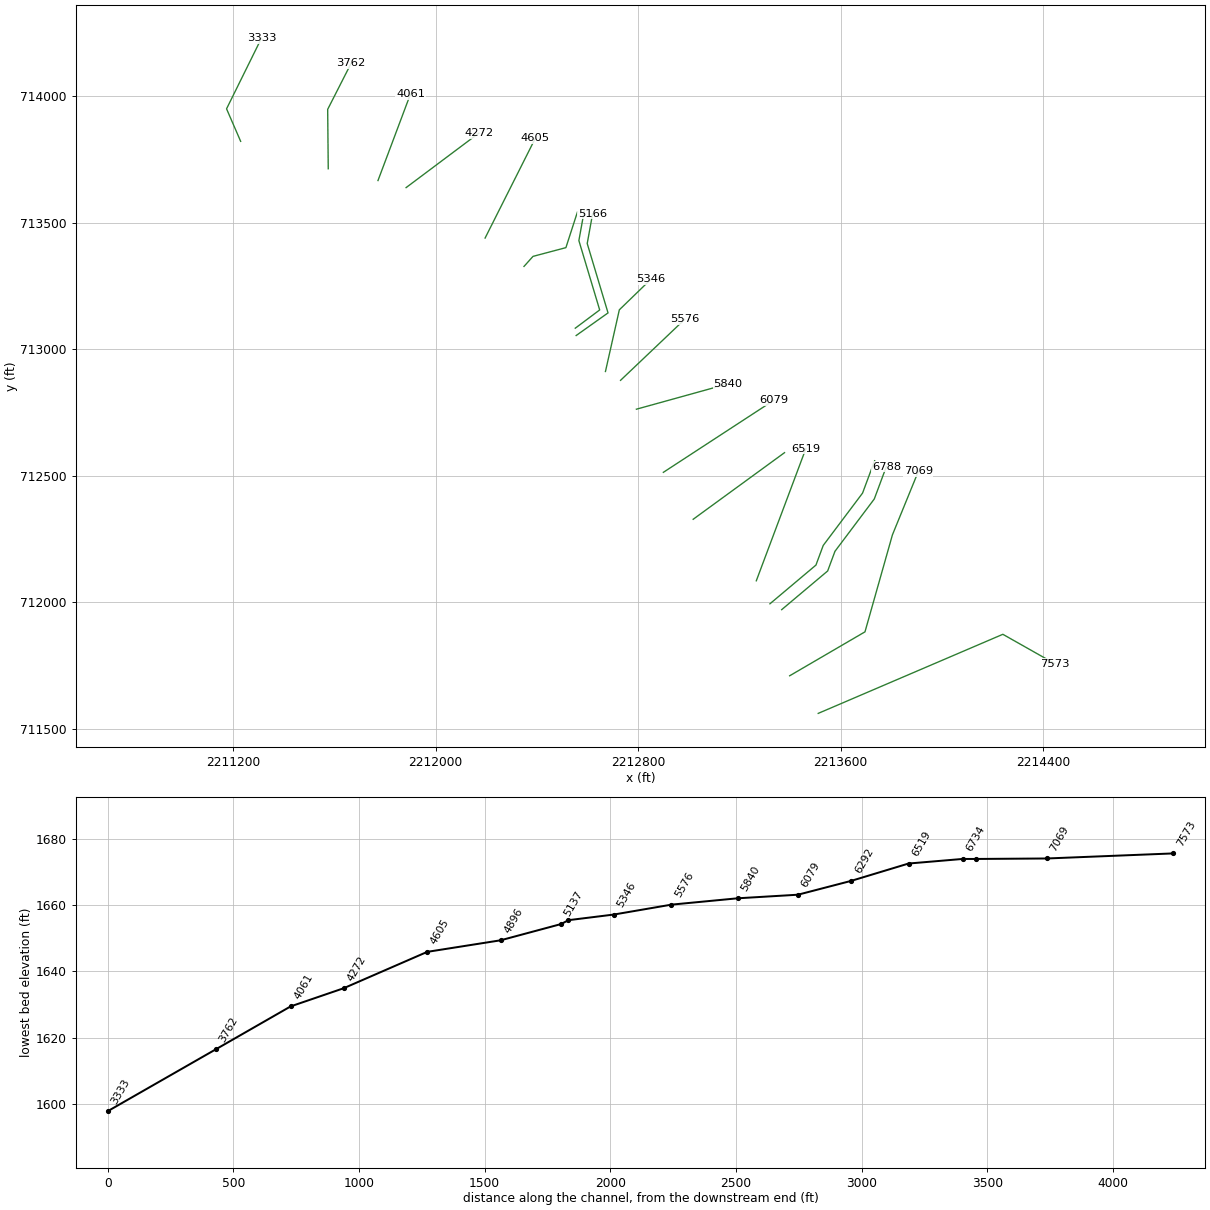
HEC-RAS study LFSANDRN.prj: LFSANDRN

--- LFSANDRN.g01 (geometry) --- (continued)

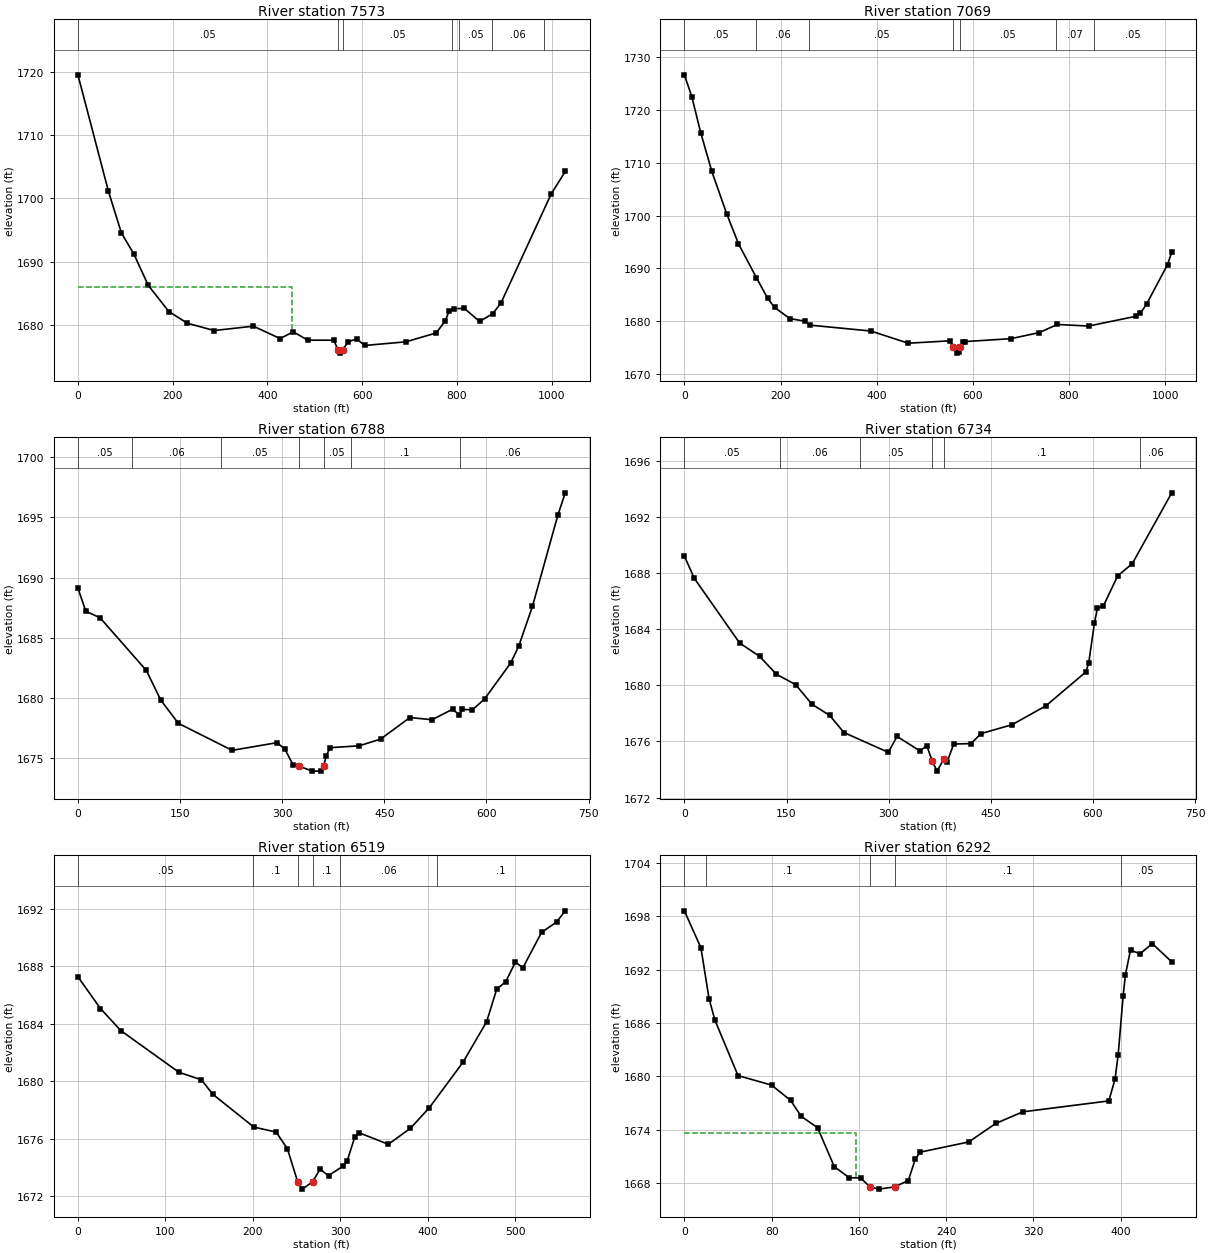
Type RM Length L Ch R = 1 ,7573    ,491.1,504.7,511.8
XS GIS Cut Line= 3
2213511.76012507711561.0200332032214241.49571587711873.530654993
2214445.73546526711758.092265458
#Sta/Elev= 30
       0 1719.53    64.4 1701.13    91.8 1694.53   117.9 1691.23   148.4 1686.27
   191.9 1682.12   231.1 1680.27   287.6 1679.12   370.3 1679.81   426.7 1677.85
   454.4 1678.92   484.9  1677.6     540 1677.59   548.5  1676.1   553.1 1675.55
  558.85  1676.1   570.5 1677.34   587.9  1677.8   605.3 1676.76   692.3 1677.34
     756 1678.74     775 1680.62   783.7 1682.28   792.9 1682.57   815.3 1682.62
   847.5 1680.56   875.3 1681.78   892.9  1683.5   998.6  1700.7  1028.4 1704.26
#Mann= 7 ,-1,0
       0     .05       0   548.5    .045       0  558.85     .05       0
     790     .06       0  803.84     .05       0  873.84     .06       0
  983.84     .05       0
#XS Ineff= 2 , 0
          450.99 1685.98
Permanent Ineff=
       F       F
Bank Sta=548.5,558.85
XS Rating Curve= 0 ,0
Exp/Cntr(USF)=0,0
Exp/Cntr=0.3,0.1

Type RM Length L Ch R = 1 ,7069    ,242.9,280.7,274.1
XS GIS Cut Line= 4
2213398.87141821711709.5906567782213696.56387577711883.252877553
2213805.05119831712266.6460644982213907.48308712712517.443922222
#Sta/Elev= 30
       0 1726.56    15.4 1722.44    33.9 1715.67    57.1 1708.33    88.4 1700.24
   112.6 1694.65     150 1688.25   173.2 1684.37   187.8 1682.64   219.2 1680.55
   251.6 1680.03   260.8 1679.31   388.2 1678.19   465.8 1675.89   553.3 1676.35
   559.7 1675.15     567 1674.02   571.1 1674.32  574.241675.126   579.4 1676.07
   583.6  1676.2   679.6 1676.75     738 1677.89   776.1 1679.43   840.9 1679.13
   939.2 1680.97   948.9 1681.55   961.9 1683.32  1005.3 1690.74    1014 1693.09
#Mann= 7 ,-1,0
       0     .05       0     150     .06       0     260     .05       0
   559.7    .045       0  574.24     .05       0  773.09     .07       0
  853.09     .05       0
Bank Sta=559.7,574.24
XS Rating Curve= 0 ,0
Exp/Cntr(USF)=0,0
Exp/Cntr=0.3,0.1

Type RM Length L Ch R = 1 ,6788    ,74.1,53.5,53.1
XS GIS Cut Line= 5
2213367.30186806711970.9228976742213549.07926413712123.866637813
2213577.91292006712201.5921450972213733.36393463712408.442285449
2213781.00214877712536.313281303
#Sta/Elev= 30
       0 1689.12    11.6 1687.19    32.5 1686.65   100.5 1682.26   121.6  1679.8
   147.5 1677.86   226.5 1675.61   292.5 1676.25     304  1675.7   315.8 1674.42
   324.9 1674.29   344.2 1673.88   357.5 1673.88     3611674.316   364.6 1675.15
   370.3 1675.83   413.2 1675.99   444.6 1676.55   487.5 1678.34   520.1 1678.16
   550.1 1679.03   560.1 1678.57   564.6 1679.02   579.2 1678.98   597.1 1679.88
   635.5 1682.88   647.3 1684.28   667.5  1687.6   704.9 1695.21   715.7 1697.05
#Mann= 7 ,-1,0
       0     .05       0      80     .06       0     210     .05       0
   324.9    .045       0     361     .05       0  400.46      .1       0
  560.46     .06       0
Bank Sta=324.9,361
XS Rating Curve= 0 ,0
Exp/Cntr(USF)=0,0
Exp/Cntr=0.3,0.1

Type RM Length L Ch R = 1 ,6734    ,211.1,214.9,218.8
XS GIS Cut Line= 5
2213320.91729114711994.115186137 2213502.6946872712147.058926276
2213531.52834313 712224.78443356 2213686.9793577712431.634573912
2213734.61757184712559.505569766
#Sta/Elev= 30
       0  1689.2    14.7 1687.61    81.1 1683.01   110.4 1682.06   135.2 1680.78
   163.5 1680.04   187.2 1678.65   213.4 1677.85   234.3 1676.63   299.5 1675.22
   312.3 1676.35     346 1675.32     356 1675.69  363.721674.631     371 1673.88
   381.2 1674.75     386 1674.55   395.5 1675.81     421 1675.84   435.5 1676.55
   481.3 1677.19   531.1 1678.54   589.4 1680.94   593.7 1681.56   602.2 1684.44
   606.5 1685.48     615 1685.62   636.4  1687.8   657.7 1688.66   715.7 1693.71
#Mann= 6 ,-1,0
       0     .05       0     140     .06       0  257.56     .05       0
  363.72    .045       0   381.2      .1       0  669.21     .06       0
Bank Sta=363.72,381.2
XS Rating Curve= 0 ,0
Exp/Cntr(USF)=0,0
Exp/Cntr=0.3,0.1

Type RM Length L Ch R = 1 ,6519    ,236.8,227.7,218.4
XS GIS Cut Line= 2
2213267.01089092712085.0038841712213462.57829635712606.516965301
#Sta/Elev= 30
       0 1687.28    25.8 1685.07    48.9 1683.54   115.5 1680.63   141.2 1680.11
     154 1679.11     201 1676.82   226.6 1676.47   239.4 1675.31  251.18 1673.01
   256.5  1672.5   268.2 1673.01   276.7 1673.88   286.4 1673.44   303.5 1674.12
   307.8 1674.48   316.3  1676.1   321.1 1676.43   354.8 1675.62   380.1 1676.74
   401.8 1678.18   440.2 1681.34   467.1 1684.15   478.7 1686.43   488.8 1686.92
     500  1688.3   508.6 1687.91   529.9 1690.37     547 1691.09     557 1691.87
#Mann= 6 ,-1,0
       0     .05       0     200      .1       0  251.18    .045       0
   268.2      .1       0     300     .06       0     410      .1       0
Bank Sta=251.18,268.2
XS Rating Curve= 0 ,0
Exp/Cntr(USF)=0,0
Exp/Cntr=0.3,0.1

Type RM Length L Ch R = 1 ,6292    ,212.8,212.3,211.1
XS GIS Cut Line= 2
2213017.53708529712328.2095037362213378.58460299 712591.47331873
#Sta/Elev= 30
       0 1698.62    15.2 1694.45    22.6 1688.73      28 1686.31    49.2 1680.07
    79.9    1679    97.3 1677.29   107.2 1675.47   122.1 1674.21   137.4 1669.83
     151 1668.58   161.7 1668.54  170.211667.535   178.2 1667.29  192.721667.543
   205.3 1668.26   211.6 1670.63   216.1 1671.45   260.7  1672.6   285.4 1674.68
   310.2 1675.99   389.1 1677.22   394.8 1679.67   397.7 1682.44   402.2 1688.98
   404.3 1691.42     409  1694.2   417.7 1693.78     429 1694.93   446.8 1692.87
#Mann= 5 ,-1,0
       0     .05       0      20      .1       0  170.21    .045       0
  192.72      .1       0     400     .05       0
#XS Ineff= 2 , 0
          156.88 1673.62
Permanent Ineff=
       F       F
Bank Sta=170.21,192.72
XS Rating Curve= 0 ,0
Exp/Cntr(USF)=0,0
Exp/Cntr=0.3,0.1

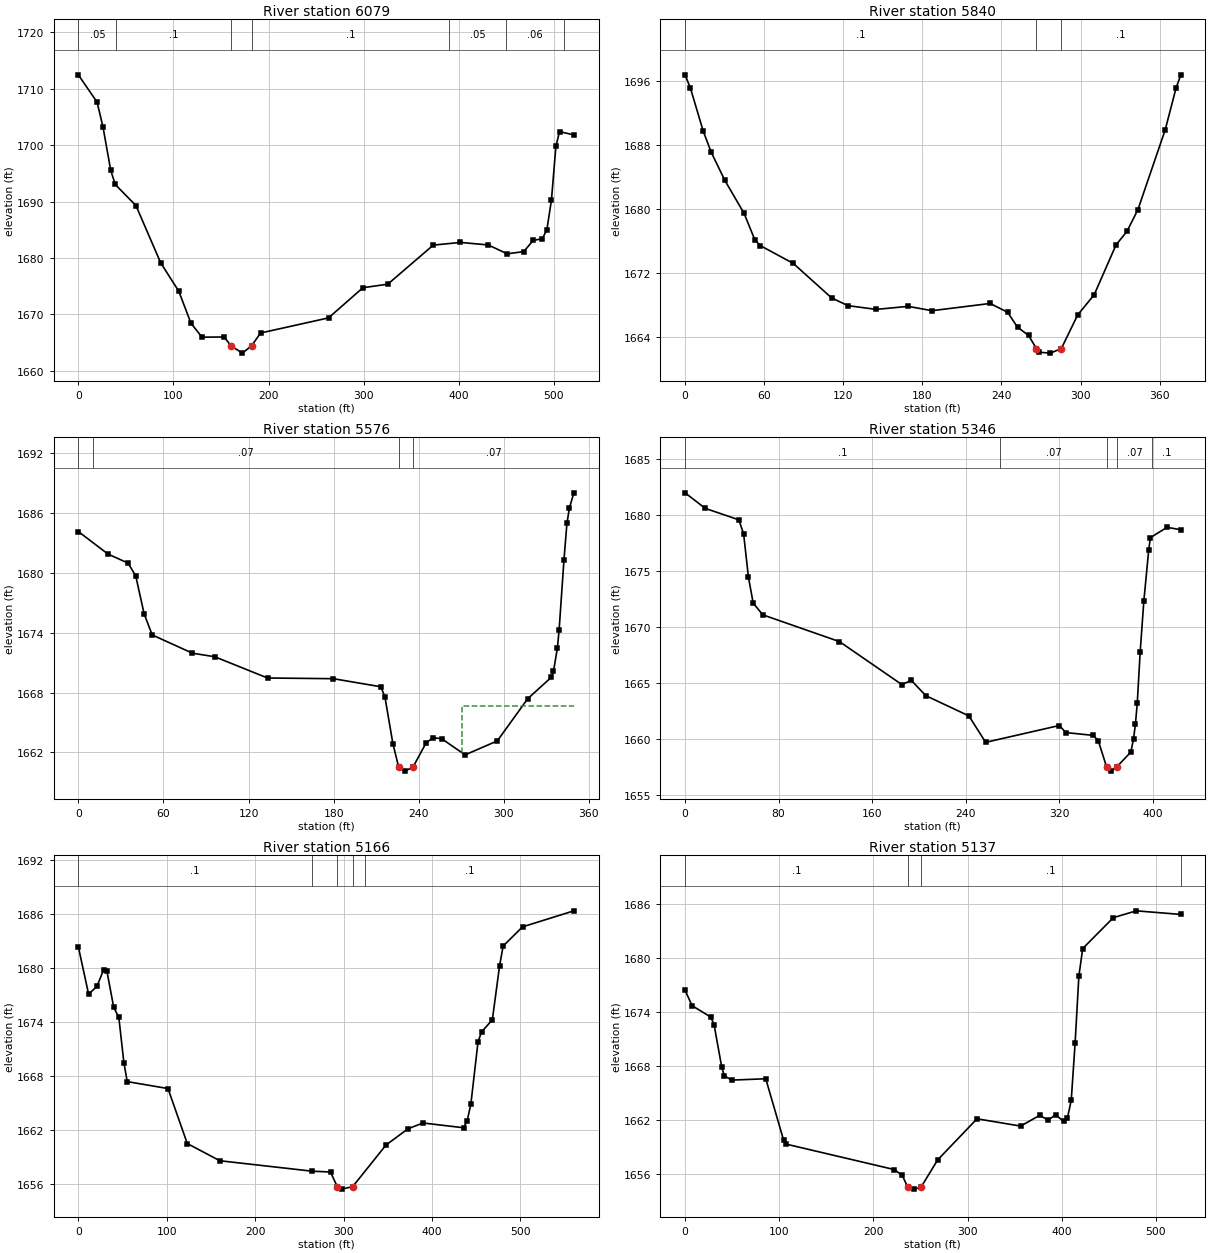
Type RM Length L Ch R = 1 ,6079    ,245.8,239.9,234.1
XS GIS Cut Line= 2
2212899.69518715712513.7478114462213335.96093771712798.323459082
#Sta/Elev= 30
       0 1712.48    19.7 1707.64    25.9 1703.26      34 1695.59    38.8 1693.03
    60.6 1689.28    86.6 1679.12   105.6 1674.09   118.4 1668.42     130 1665.94
   153.4 1665.97  160.461664.398   172.5 1663.11   182.1 1664.41   191.6 1666.68
     263 1669.36   299.1 1674.71   325.3 1675.34   373.1 1682.27   401.7 1682.75
   430.9  1682.3   450.8 1680.73   468.2 1681.12   478.1  1683.1   487.7 1683.41
   492.5 1684.99   497.3 1690.22     502 1699.79   505.8 1702.41   520.9 1701.82
#Mann= 7 ,-1,0
       0     .05       0      40      .1       0  160.46    .045       0
   182.1      .1       0     390     .05       0     450     .06       0
     510      .1       0
Bank Sta=160.46,182.1
XS Rating Curve= 0 ,0
Exp/Cntr(USF)=0,0
Exp/Cntr=0.3,0.1

Type RM Length L Ch R = 1 ,5840    ,258.4,263.3,272.1
XS GIS Cut Line= 2
2212793.13602394712763.2216170832213155.43717885712863.512594223
#Sta/Elev= 30
       0 1696.72     4.1 1695.04    13.8 1689.68    19.8 1687.08    30.1 1683.58
    44.7 1679.47      53 1676.12    57.1 1675.43    82.1 1673.21   111.1 1668.92
   123.5 1667.95     145 1667.48   169.2 1667.86   187.3 1667.32   231.4 1668.22
   244.6 1667.13   252.2 1665.26   260.5 1664.24  266.56 1662.59   268.8 1662.14
   277.1 1662.03   285.4  1662.6   297.8 1666.79   310.3  1669.3   326.9 1675.52
   335.2 1677.21   343.5 1679.92   364.2 1689.87   372.5 1695.12   375.9 1696.64
#Mann= 3 ,-1,0
       0      .1       0  266.56    .045       0   285.4      .1       0
Bank Sta=266.56,285.4
XS Rating Curve= 0 ,0
Exp/Cntr(USF)=0,0
Exp/Cntr=0.3,0.1

Type RM Length L Ch R = 1 ,5576    ,229.3,229.8,229
XS GIS Cut Line= 2
2212730.45416322 712877.30260358 2212983.6888805713118.000948717
#Sta/Elev= 30
       0 1684.15    20.9 1681.89    35.1 1680.98    40.5 1679.69    46.4 1675.89
    52.1 1673.78    80.4 1671.95    96.2 1671.59   133.4 1669.46   179.8 1669.39
   213.3 1668.58   216.2 1667.54   221.8 1662.87   225.91660.506   230.3 1660.12
     236 1660.53   245.2 1662.95   250.1 1663.47   256.2 1663.37   272.7 1661.75
   295.4 1663.15   316.9 1667.39   333.5 1669.53     335 1670.12   337.8 1672.48
     339  1674.3   342.4 1681.28   344.5 1684.97   346.3 1686.54   349.4 1688.03
#Mann= 4 ,-1,0
       0      .1       0      10     .07       0   225.9    .045       0
     236     .07       0
#XS Ineff= 1 ,-1
   270.3349.3759  1666.7
Permanent Ineff=
       F
Bank Sta=225.9,236
XS Rating Curve= 0 ,0
Exp/Cntr(USF)=0,0
Exp/Cntr=0.3,0.1

Type RM Length L Ch R = 1 ,5346    ,168.3,180.3,192.8
XS GIS Cut Line= 3
2212670.83117731712912.3292273462212725.66526906713156.036301798
2212850.80333579713277.212874928
#Sta/Elev= 30
       0 1681.97    17.3 1680.58      46 1679.56    50.1  1678.3    54.2 1674.44
    58.3 1672.12    66.5 1671.08   132.1 1668.69   185.4 1664.86   193.6 1665.23
   205.9 1663.87   242.8 1662.06   257.2  1659.7   320.1  1661.2   325.9 1660.57
   349.2 1660.32   353.5 1659.85   360.7 1657.49   364.7 1657.13  369.191657.492
   381.4 1658.83   383.7 1660.01   385.3 1661.31   386.9 1663.22   389.4  1667.8
   392.5 1672.29   396.7 1676.88   398.1 1677.97   412.4 1678.89     424 1678.68
#Mann= 5 ,-1,0
       0      .1       0   269.8     .07       0   360.7    .045       0
  369.19     .07       0   399.8      .1       0
Bank Sta=360.7,369.19
XS Rating Curve= 0 ,0
Exp/Cntr(USF)=0,0
Exp/Cntr=0.3,0.1

Type RM Length L Ch R = 1 ,5166    ,28.9,28.7,29
XS GIS Cut Line= 4
2212555.07031695713054.4916874432212680.98563875713143.850948075
2212598.73450112713418.0214068332212620.05887014713535.813159484
#Sta/Elev= 30
       0 1682.34    11.6 1677.08      21 1677.93    28.5 1679.75    32.3 1679.65
      40 1675.62    45.8  1674.5    51.5 1669.49    55.3 1667.37   101.4  1666.6
   123.2  1660.5     160 1658.59   264.4 1657.43   285.2 1657.34  292.91 1655.69
   297.8 1655.44   310.3 1655.72   347.9 1660.33   372.9 1662.14   389.7 1662.78
   435.6 1662.25   439.8 1663.05   443.9 1664.87     452 1671.78     456 1672.88
   468.2 1674.23   476.4 1680.24   480.4 1682.41   502.3 1684.54   560.4 1686.32
#Mann= 5 ,-1,0
       0      .1       0   264.4     .06       0  292.91    .045       0
   310.3     .06       0   324.4      .1       0
Bank Sta=292.91,310.3
XS Rating Curve= 0 ,0
Exp/Cntr(USF)=0,0
Exp/Cntr=0.3,0.1

Type RM Length L Ch R = 1 ,5137    ,260.8,241,220.5
XS GIS Cut Line= 4
2212551.51625545713083.4319025342212647.98363908713155.528578726
2212565.73250146713429.6990374832212587.05687047713547.490790135
#Sta/Elev= 30
       0 1676.39     7.4 1674.68    27.4  1673.4    30.8 1672.56    38.9 1667.86
    41.7 1666.87    49.7  1666.4    85.7 1666.55   104.6 1659.74   107.5 1659.28
   222.4 1656.45   230.7  1655.8   236.5 1654.51   243.3 1654.28  250.651654.498
   268.3 1657.53   310.1  1662.1   356.4 1661.29   376.9 1662.49   385.3 1661.95
   393.6 1662.52     402 1661.84   406.1 1662.15   410.2 1664.17   414.3 1670.51
   418.3 1677.97   422.4 1681.03   454.9 1684.46   479.3 1685.22   526.4 1684.82
#Mann= 4 ,-1,0
       0      .1       0   236.5    .045       0  250.65      .1       0
  526.38     .07       0
Bank Sta=236.5,250.65
XS Rating Curve= 0 ,0
Exp/Cntr(USF)=0,0
Exp/Cntr=0.3,0.1

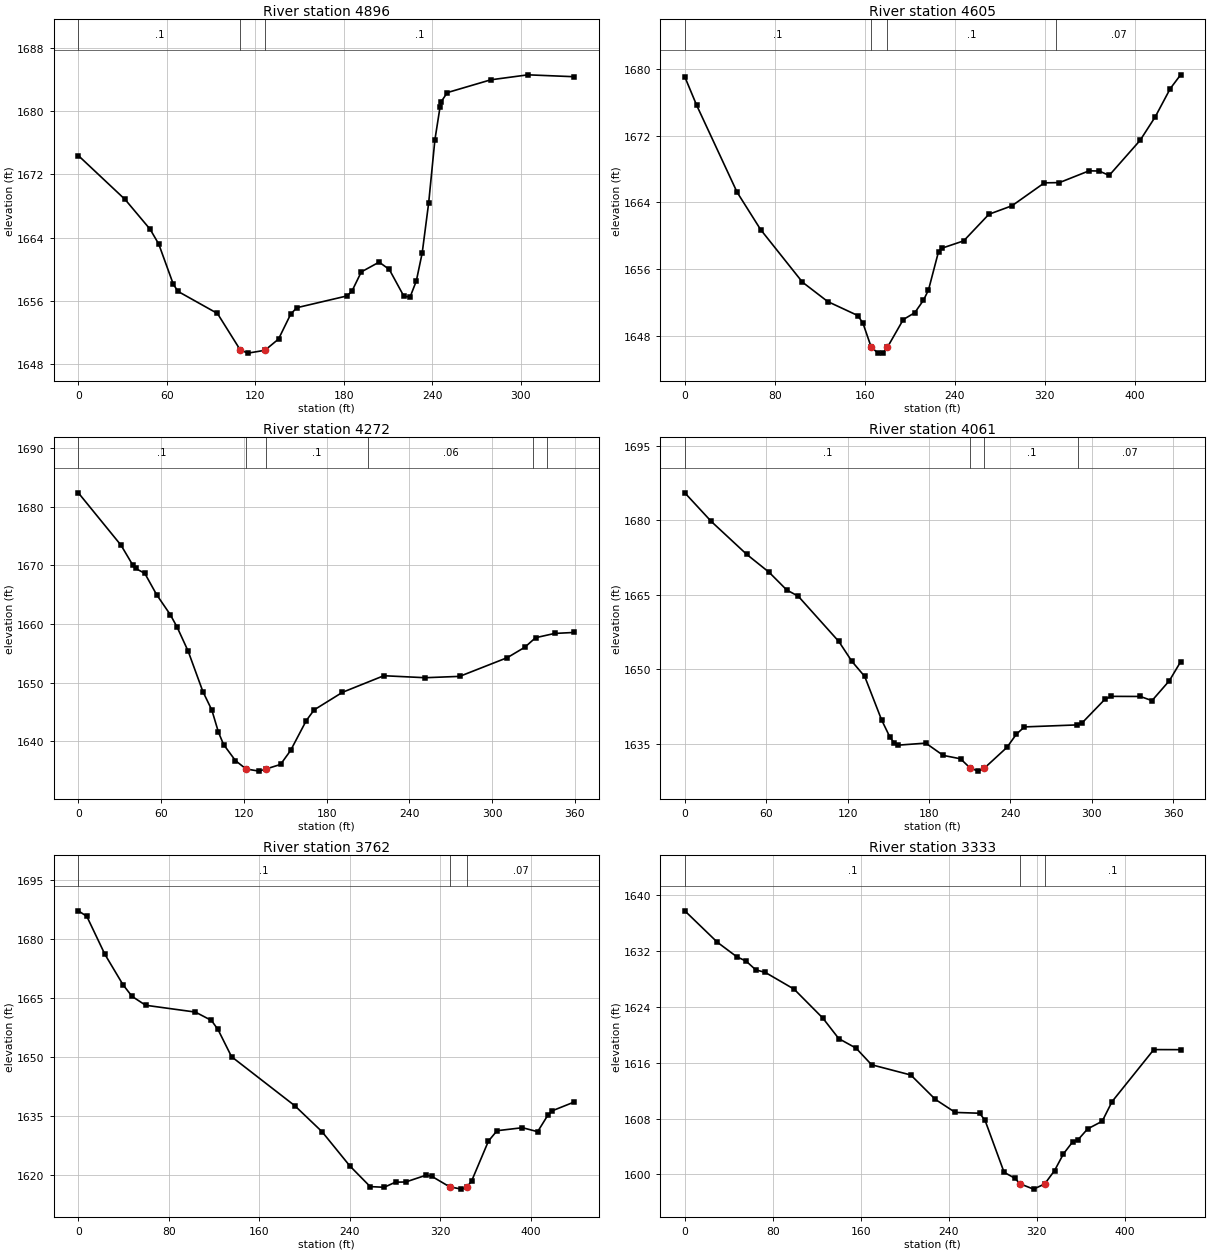
Type RM Length L Ch R = 1 ,4896    ,279,291.7,300.9
XS GIS Cut Line= 4
2212348.93474981713327.6467000572212384.47536483713367.249099655
2212514.45247121713401.7742685362212560.14754767713542.921282489
#Sta/Elev= 30
       0 1674.39    31.7 1668.83    48.7 1665.05    54.5 1663.19    64.4 1658.09
    67.6 1657.19    94.3  1654.4  109.81 1649.77     115 1649.38   126.5 1649.74
   135.7 1651.16     144 1654.33   148.1 1655.13   182.1 1656.62   185.4  1657.2
   191.8 1659.66   203.9  1660.9   210.8 1659.97   220.7 1656.57   224.9 1656.49
   229.1 1658.51   233.1 1662.07   237.5 1668.43   241.7 1676.38   245.2 1680.55
   245.9 1681.19   250.1 1682.36   279.6 1683.98   304.8 1684.61   336.1 1684.37
#Mann= 3 ,-1,0
       0      .1       0  109.81    .045       0   126.5      .1       0
Bank Sta=109.81,126.5
XS Rating Curve= 0 ,0
Exp/Cntr(USF)=0,0
Exp/Cntr=0.3,0.1

Type RM Length L Ch R = 1 ,4605    ,338.4,333,327.8
XS GIS Cut Line= 2
2212195.15107274713439.7093306392212393.22575259713833.351415915
#Sta/Elev= 30
       0 1679.05    10.6 1675.62    46.5  1665.2    67.4 1660.72   104.6 1654.41
     127 1652.09   153.9  1650.4   158.4 1649.47   165.7 1646.61   171.8  1645.9
   176.3 1645.94  180.051646.594   194.2 1649.93   204.4 1650.75   212.1 1652.24
   216.6 1653.48   225.5 1658.07   228.3 1658.48   247.9 1659.37   270.3 1662.56
   290.8 1663.58   319.6 1666.33     333 1666.36   359.3 1667.77   368.3 1667.75
   377.2 1667.22   404.7 1671.43   418.1 1674.24   431.5 1677.64   440.7 1679.29
#Mann= 4 ,-1,0
       0      .1       0   165.7    .045       0  180.05      .1       0
     330     .07       0
Bank Sta=165.7,180.05
XS Rating Curve= 0 ,0
Exp/Cntr(USF)=0,0
Exp/Cntr=0.3,0.1

Type RM Length L Ch R = 1 ,4272    ,204.1,210.6,216.3
XS GIS Cut Line= 2
2211882.87004266713639.0376477062212170.57978334713854.537884836
#Sta/Elev= 30
       0 1682.39      31 1673.44    39.6 1670.02    41.6 1669.49    48.2 1668.65
    56.8 1665.01    66.6 1661.64    71.6  1659.5    79.6  1655.4    90.3  1648.5
    96.8 1645.34   101.6 1641.56   105.3 1639.47   113.9 1636.73   121.6  1635.3
     131 1634.93  135.941635.284   146.6 1636.07   153.9 1638.45   165.3 1643.56
     171 1645.38   191.5 1648.37   221.5  1651.2   251.5 1650.86   276.5 1651.09
   311.1 1654.29   323.8 1656.07   331.5 1657.68   345.3 1658.41   359.5 1658.58
#Mann= 6 ,-1,0
       0      .1       0   121.6    .045       0  135.94      .1       0
     210     .06       0     330     .07       0     340     .05       0
Bank Sta=121.6,135.94
XS Rating Curve= 0 ,0
Exp/Cntr(USF)=0,0
Exp/Cntr=0.3,0.1

Type RM Length L Ch R = 1 ,4061    ,296.3,298.7,295.9
XS GIS Cut Line= 2
2211771.74934117713666.9056453982211900.20846313714008.947403855
#Sta/Elev= 30
       0 1685.49    19.5 1679.73    45.6 1673.11    62.2 1669.48    75.1 1665.94
    83.6 1664.68   113.5 1655.57   123.2 1651.55   132.6 1648.52     145  1639.8
   151.2 1636.29   154.3 1635.17   157.4  1634.7   177.6 1635.11   190.4 1632.64
   203.2 1631.95   210.2 1630.12   216.1 1629.47  220.811630.083   237.4 1634.25
   244.4 1636.92   250.3 1638.37   288.7 1638.77     293 1639.24   309.6 1643.93
   314.3 1644.52   335.7  1644.5   344.3 1643.66   357.1 1647.67   365.4 1651.48
#Mann= 4 ,-1,0
       0      .1       0   210.2    .045       0  220.81      .1       0
     290     .07       0
Bank Sta=210.2,220.81
XS Rating Curve= 0 ,0
Exp/Cntr(USF)=0,0
Exp/Cntr=0.3,0.1

Type RM Length L Ch R = 1 ,3762    ,421.2,429.2,421.6
XS GIS Cut Line= 3
2211575.16664438713713.6508364872211572.91009739713948.331722996
 2211665.4285238714129.983755341
#Sta/Elev= 30
       0 1687.09     7.5 1685.69    23.5 1676.05    39.5 1668.35    47.5 1665.39
    59.5 1663.14   103.5 1661.41   117.7 1659.29   123.5 1656.99   135.5 1650.09
   191.5 1637.64   215.5 1631.07   240.1 1622.39   258.1 1617.14   270.5 1616.97
   280.5 1618.27   289.5 1618.31   307.5 1620.03   312.4 1619.78  328.361617.086
   338.8  1616.5  343.861617.094   347.9 1618.62   362.7 1628.69   370.3 1631.32
   392.8 1632.08   406.2 1631.07   415.2 1635.24   419.2 1636.38   438.5 1638.59
#Mann= 3 ,-1,0
       0      .1       0  328.36    .045       0  343.86     .07       0
Bank Sta=328.36,343.86
XS Rating Curve= 0 ,0
Exp/Cntr(USF)=0,0
Exp/Cntr=0.3,0.1

Type RM Length L Ch R = 1 ,3333    ,405.2,411.4,407.6
XS GIS Cut Line= 3
2211228.94609521713822.0115228062211173.22888568713950.470644761
2211310.97420922714229.056692373
#Sta/Elev= 30
       0 1637.75    29.6 1633.25    47.1 1631.19    55.8 1630.54    64.5  1629.3
    73.2 1628.93    99.4 1626.53   125.5 1622.39     140 1619.45   155.7 1618.09
   169.8 1615.71   205.5 1614.24   227.8 1610.75   245.9 1608.88     268 1608.77
     273 1607.74   290.3 1600.31   300.1 1599.46  304.79 1598.66   317.1  1597.9
   327.2 1598.64   336.2 1600.56   344.3 1602.96   352.8  1604.7   357.2 1604.91
   366.2 1606.52   379.5 1607.62   388.5 1610.44   426.4 1617.88   450.8 1617.87
#Mann= 3 ,-1,0
       0      .1       0  304.79    .045       0   327.2      .1       0
Bank Sta=304.79,327.2
XS Rating Curve= 0 ,0
Exp/Cntr(USF)=0,0
Exp/Cntr=0.3,0.1