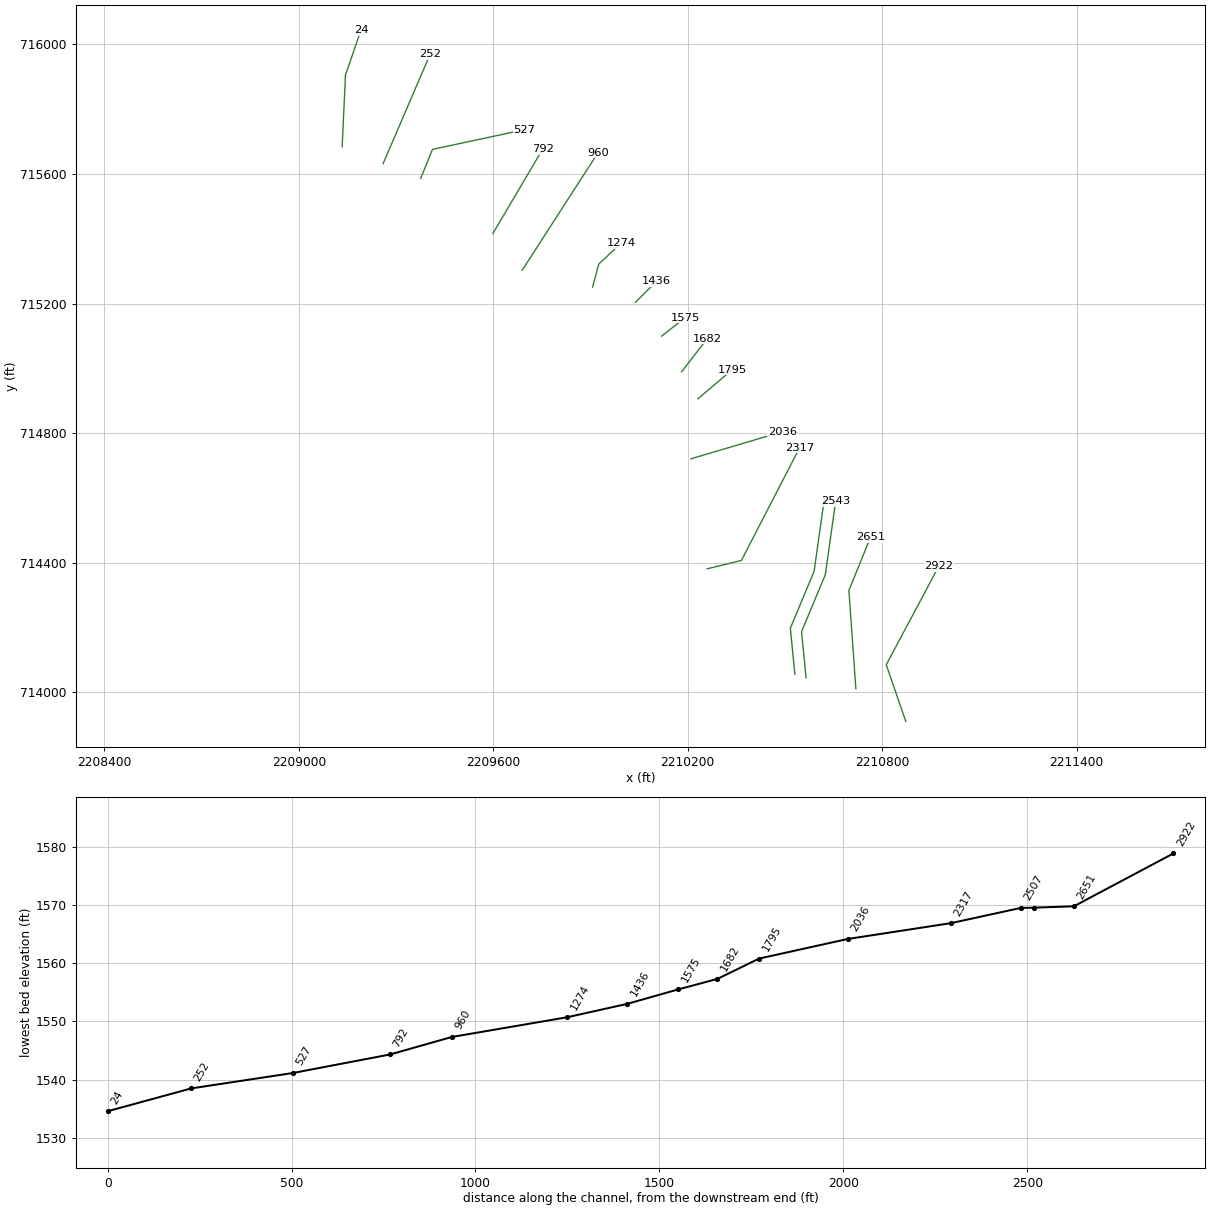
HEC-RAS study LFSANDRN.prj: LFSANDRN

--- LFSANDRN.g01 (geometry) --- (continued)

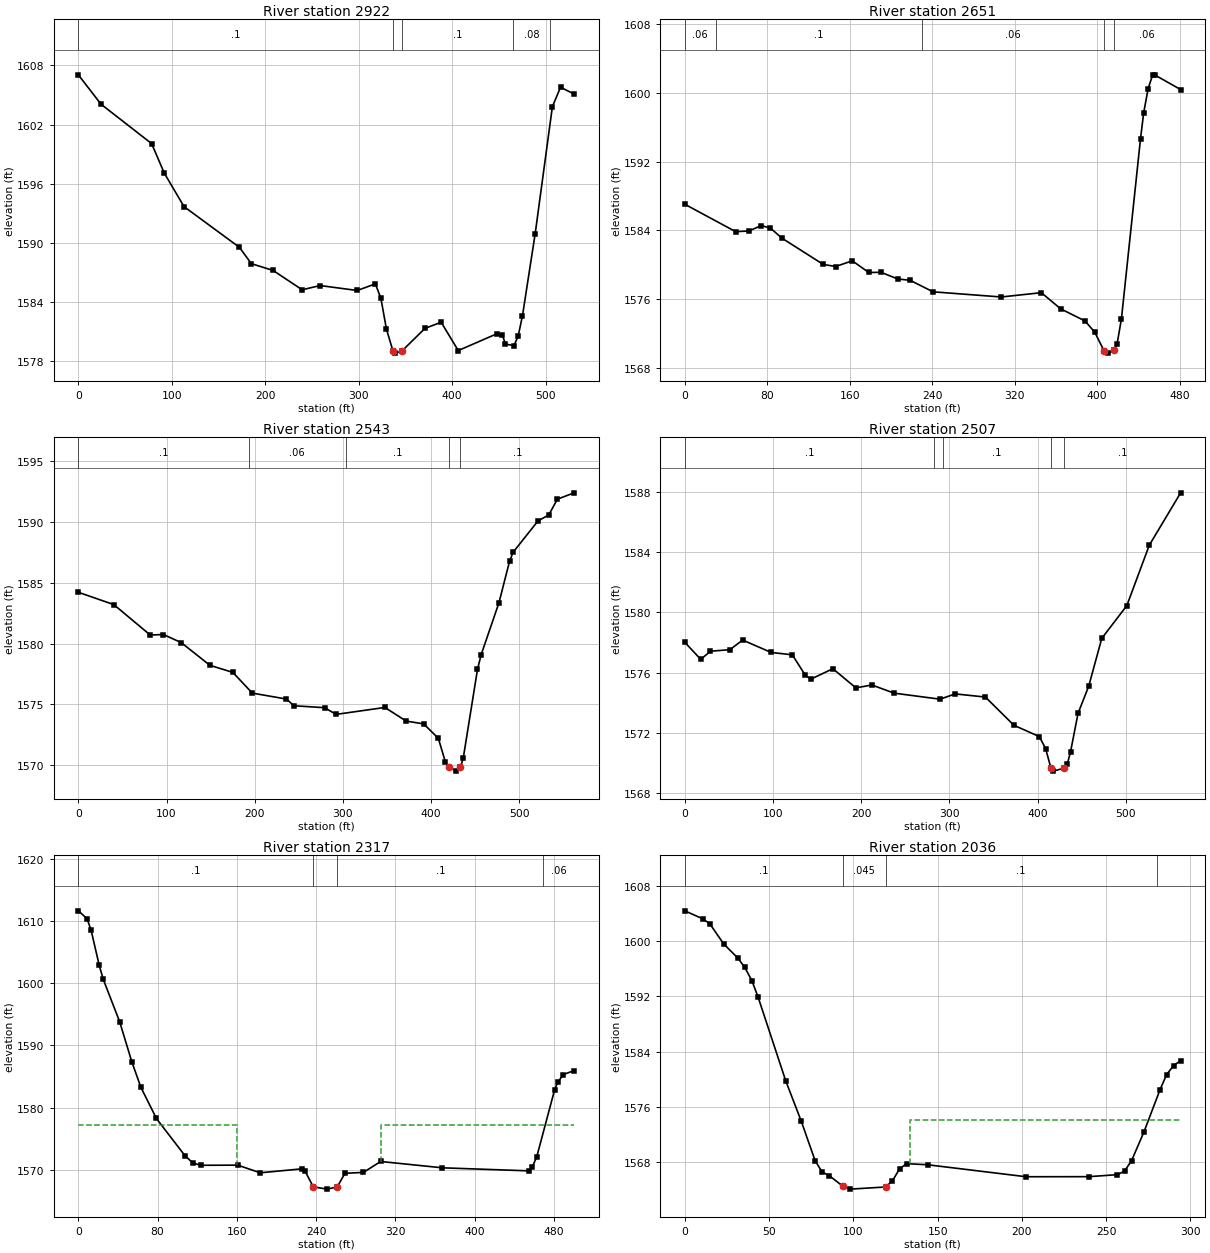
Type RM Length L Ch R = 1 ,2922    ,266.4,270.7,268.2
XS GIS Cut Line= 3
2210872.97503437713910.2304378842210812.61472405714085.120567774
2210975.12325183714390.017519883
#Sta/Elev= 30
       0 1607.04    24.3 1604.06    78.4 1600.07      92 1597.07   113.1 1593.68
   172.4 1589.55   185.1  1587.9   208.4 1587.21   239.5 1585.25   258.7 1585.68
   298.4 1585.18   317.8 1585.85   323.7  1584.4   329.6 1581.29  336.591579.055
   339.2 1578.83  346.211579.042   370.9 1581.34   388.2 1581.96   406.5 1579.09
     448  1580.8   453.8 1580.65     457 1579.74   466.1  1579.6   470.6 1580.55
   475.2 1582.62   488.8 1590.94   507.2 1603.81   515.9 1605.78   530.5 1605.09
#Mann= 5 ,-1,0
       0      .1       0  336.59    .045       0  346.21      .1       0
  465.01     .08       0  505.01     .06       0
Bank Sta=336.59,346.21
XS Rating Curve= 0 ,0
Exp/Cntr(USF)=0,0
Exp/Cntr=0.3,0.1

Type RM Length L Ch R = 1 ,2651    ,105.9,108,111.6
XS GIS Cut Line= 3
2210718.85504203714011.2287140452210697.41784566714314.734283616
2210763.98598174714478.333940077
#Sta/Elev= 30
       0 1587.04    49.3 1583.86    62.1 1583.93    74.1 1584.56      83 1584.28
    94.2  1583.1   134.3 1580.05   146.3 1579.81   162.4 1580.47   178.4 1579.12
   190.4 1579.13   206.6 1578.36   218.5 1578.21   240.8 1576.87   306.9 1576.27
   345.8 1576.77   364.6 1574.89   388.1 1573.49   397.6 1572.18   406.5 1570.05
   410.5 1569.75  415.98 1570.06   419.2 1570.76   423.5 1573.74     442 1594.66
   445.1 1597.68   449.4 1600.47   453.7 1602.04   455.6 1602.07   480.9 1600.36
#Mann= 5 ,-1,0
       0     .06       0      30      .1       0     230     .06       0
   406.5    .045       0  415.98     .06       0
Bank Sta=406.5,415.98
XS Rating Curve= 0 ,0
Exp/Cntr(USF)=0,0
Exp/Cntr=0.3,0.1

Type RM Length L Ch R = 1 ,2543    ,35.9,36.6,36.3
XS GIS Cut Line= 4
 2210565.2439908714045.176206897 2210551.2612974714187.470674993
2210624.46480989714362.6655981392210656.54275357 714589.67873799
#Sta/Elev= 30
       0 1584.21    40.2  1583.2    81.5  1580.7    96.5 1580.74   116.6 1580.08
   149.2 1578.21   175.2 1577.63   197.2 1575.93   235.9 1575.44   244.5 1574.89
   279.2 1574.73   292.2 1574.18   347.5 1574.75   371.7 1573.63   391.5  1573.4
   408.1 1572.22   416.2 1570.25   420.2 1569.86   428.3 1569.52  433.151569.822
   436.4  1570.6   452.5 1577.87   456.6 1579.07   476.8 1583.34   488.9 1586.77
   492.9  1587.5   521.2 1590.08   533.3 1590.56   543.1 1591.86   562.1 1592.38
#Mann= 5 ,-1,0
       0      .1       0  192.98     .06       0  302.98      .1       0
   420.2    .045       0  433.15      .1       0
Bank Sta=420.2,433.15
XS Rating Curve= 0 ,0
Exp/Cntr(USF)=0,0
Exp/Cntr=0.3,0.1

Type RM Length L Ch R = 1 ,2507    ,195.1,189.7,185.1
XS GIS Cut Line= 4
  2210530.698513714055.868854789 2210516.7158196714198.163322884
2210589.91933209 714373.358246032210621.99727576714600.371385882
#Sta/Elev= 30
       0 1578.01    18.1 1576.88    29.1 1577.42    51.1 1577.52    65.6 1578.16
    97.8 1577.34   121.9 1577.18   136.8 1575.81     143 1575.57   167.9 1576.26
   193.9 1574.99   212.1 1575.18   237.3 1574.64   289.3 1574.24   306.6 1574.59
   340.8 1574.38   373.1 1572.51   401.9 1571.76     409 1570.97  415.091569.668
   417.5 1569.47   430.3 1569.67   433.7 1569.96   437.3 1570.75   445.8  1573.3
   457.9  1575.1   472.7 1578.27   501.1 1580.44   526.6 1584.45   562.1 1587.92
#Mann= 5 ,-1,0
       0      .1       0  282.98     .06       0  292.98      .1       0
  415.09    .045       0   430.3      .1       0
Bank Sta=415.09,430.3
XS Rating Curve= 0 ,0
Exp/Cntr(USF)=0,0
Exp/Cntr=0.3,0.1

Type RM Length L Ch R = 1 ,2317    ,294.3,280.7,266.7
XS GIS Cut Line= 3
2210259.65337181714381.2347232842210365.71108014714407.185013619
 2210545.1065655 714754.69324941
#Sta/Elev= 30
       0 1611.66     8.8  1610.4    12.9 1608.53    21.1 1602.87    25.2 1600.61
    41.7  1593.8    54.1 1587.29    63.2 1583.22    78.8 1578.23   107.6 1572.24
   115.5 1571.08   123.3  1570.7   160.9 1570.72   183.5 1569.49   225.3 1570.12
   228.5 1569.85  237.021567.229     251 1566.86  261.291567.222     269 1569.41
   287.7 1569.55     305 1571.31   367.4 1570.29   454.6  1569.8     458 1570.39
   462.6 1572.09   480.6 1582.86   483.6 1584.04   489.5 1585.31   500.3 1585.95
#Mann= 4 ,-1,0
       0      .1       0  237.02    .045       0  261.29      .1       0
  469.19     .06       0
#XS Ineff= 2 ,-1
  -38.82  159.861577.222  304.95500.2678 1577.23
Permanent Ineff=
       F       F
Bank Sta=237.02,261.29
XS Rating Curve= 0 ,0
Exp/Cntr(USF)=0,0
Exp/Cntr=0.3,0.1

Type RM Length L Ch R = 1 ,2036    ,237.9,240.7,237.6
XS GIS Cut Line= 2
2210210.00933813714720.8450446252210492.07771134714804.337283095
#Sta/Elev= 30
       0 1604.35    10.6  1603.2    14.8 1602.49    23.1 1599.56    31.5 1597.52
    35.6 1596.17    39.8 1594.26    43.5 1591.88    59.9 1579.78      69 1574.02
    77.3 1568.27    81.5  1566.6    85.7 1566.09      94 1564.52    98.2 1564.14
   119.1 1564.45   123.2 1565.33   127.4 1567.06   131.6 1567.82   144.1 1567.66
   202.5 1565.93   239.7 1565.94   256.7 1566.23   260.9 1566.74   265.1 1568.26
   272.4 1572.38     282 1578.52   285.9  1580.7   290.1    1582   294.2 1582.71
#Mann= 4 ,-1,0
       0      .1       0      94    .045       0   119.1      .1       0
     280     .06       0
#XS Ineff= 1 ,-1
  133.33294.1658  1574.1
Permanent Ineff=
       F
Bank Sta=94,119.1
XS Rating Curve= 0 ,0
Exp/Cntr(USF)=0,0
Exp/Cntr=0.3,0.1

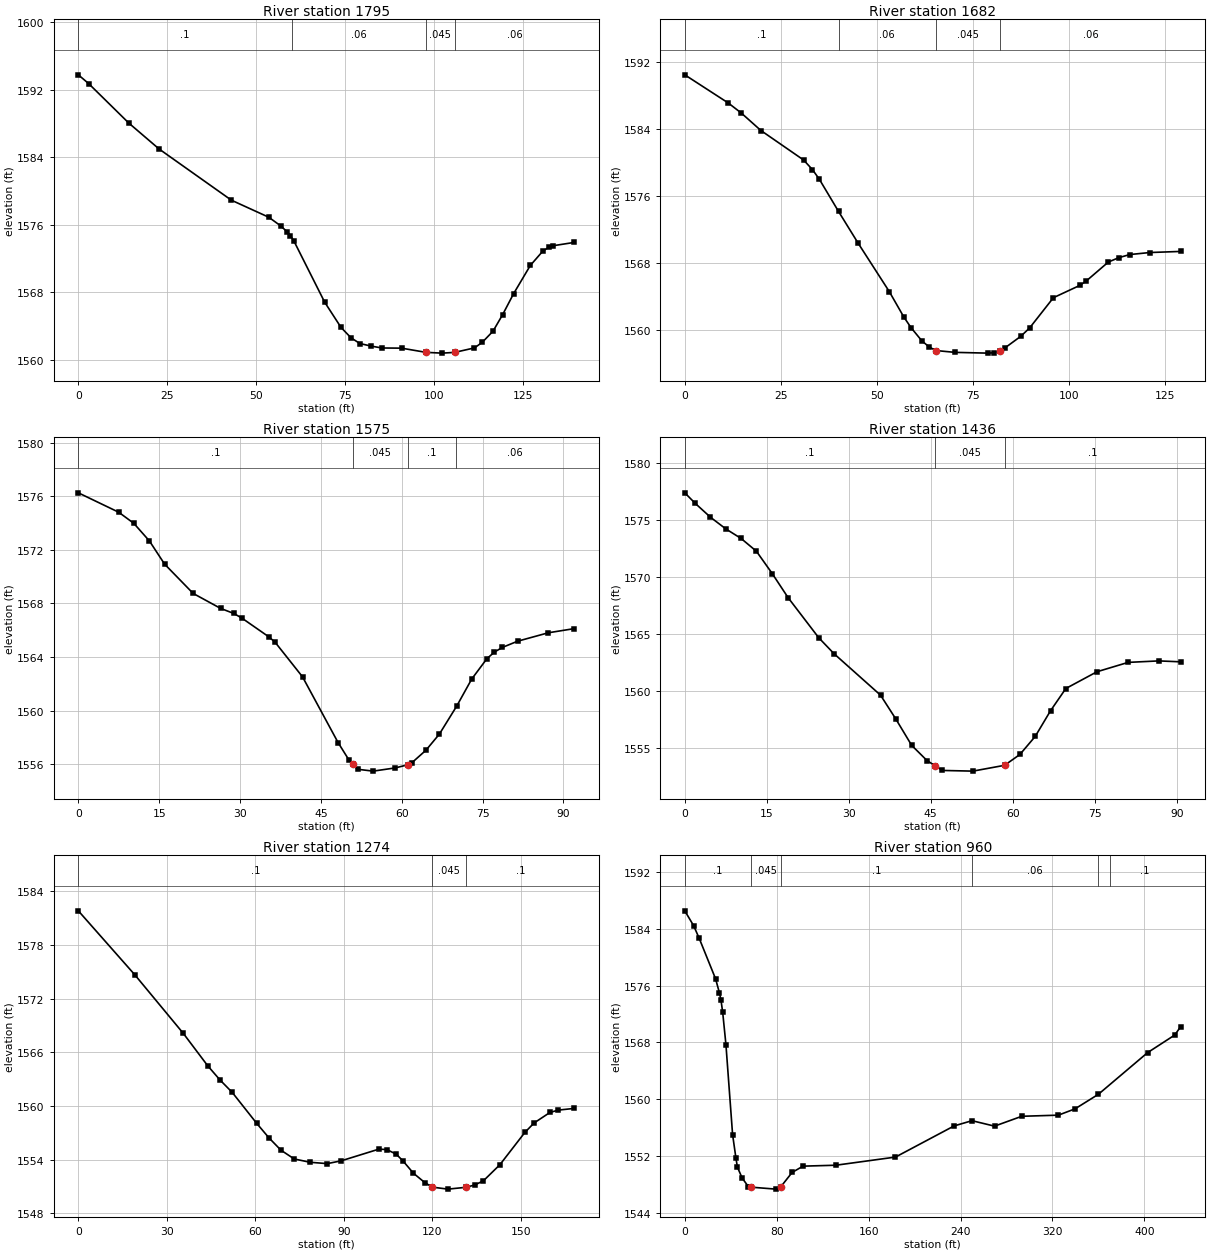
Type RM Length L Ch R = 1 ,1795    ,110.9,113.3,115.3
XS GIS Cut Line= 2
2210231.44653449 714905.881897452210337.50424282714996.143776876
#Sta/Elev= 30
       0 1593.79     2.9 1592.75    14.2 1588.06    22.7 1584.99      43 1578.92
    53.5  1576.9    56.8 1575.89    58.7 1575.16    59.6 1574.71    60.6 1574.05
    69.2 1566.83    73.8 1563.83    76.6  1562.6    79.1 1561.92    82.3 1561.61
    85.3 1561.39    90.8 1561.37    97.7 1560.87   102.2 1560.78  105.691560.865
   111.3  1561.4   113.5 1562.07   116.5 1563.38   119.2 1565.34   122.3 1567.84
     127 1571.19   130.5 1572.88   132.3 1573.37   133.4 1573.52   139.3 1573.91
#Mann= 4 ,-1,0
       0      .1       0      60     .06       0    97.7    .045       0
  105.69     .06       0
Bank Sta=97.7,105.69
XS Rating Curve= 0 ,0
Exp/Cntr(USF)=0,0
Exp/Cntr=0.3,0.1

Type RM Length L Ch R = 1 ,1682    ,110.4,107.1,103.6
XS GIS Cut Line= 2
2210181.26431435714989.5208114732210260.22540647715091.512222131
#Sta/Elev= 30
       0 1590.43    11.3 1587.08    14.7 1585.88    19.8  1583.8    30.9 1580.29
    33.2 1579.15      35    1578      40 1574.16    45.1 1570.38    53.2 1564.62
      57 1561.58    58.9  1560.3    61.7 1558.74    63.6 1558.02    65.3  1557.6
    70.3 1557.38    78.8 1557.29    80.5 1557.34   82.021557.589    83.2 1557.88
    87.4 1559.29    89.7 1560.28    95.9 1563.89   102.8 1565.36   104.5  1565.9
   110.2 1568.14     113 1568.67   115.8 1569.03     121 1569.27     129  1569.4
#Mann= 4 ,-1,0
       0      .1       0      40     .06       0    65.3    .045       0
   82.02     .06       0
Bank Sta=65.3,82.02
XS Rating Curve= 0 ,0
Exp/Cntr(USF)=0,0
Exp/Cntr=0.3,0.1

Type RM Length L Ch R = 1 ,1575    ,137.2,138.6,139.9
XS GIS Cut Line= 2
2210119.43868786715099.4254309552210191.81968897715156.178715918
#Sta/Elev= 30
       0 1576.26     7.5 1574.81    10.3 1573.98    13.2 1572.66      16 1570.94
    21.3 1568.75    26.4 1567.63    28.8 1567.26    30.3 1566.92    35.3 1565.52
    36.5 1565.11    41.6 1562.52    48.2 1557.61    50.2 1556.32   50.911556.009
    51.8 1555.62    54.7 1555.48    58.8 1555.72    61.2 1555.96    61.9 1556.11
    64.5 1557.04      67 1558.25    70.2 1560.33      73 1562.36    75.8 1563.87
    77.2 1564.37    78.7 1564.72    81.5 1565.18    87.2 1565.81      92 1566.12
#Mann= 4 ,-1,0
       0      .1       0   50.91    .045       0    61.2      .1       0
      70     .06       0
Bank Sta=50.91,61.2
XS Rating Curve= 0 ,0
Exp/Cntr(USF)=0,0
Exp/Cntr=0.3,0.1

Type RM Length L Ch R = 1 ,1436    ,162.9,162.7,162.2
XS GIS Cut Line= 2
2210038.83257298715203.8843757412210102.98846033715268.040263091
#Sta/Elev= 26
       0 1577.39     1.9 1576.47     4.7 1575.25     7.5 1574.23    10.3 1573.39
    13.1 1572.27      16 1570.31    18.9  1568.2    24.5 1564.69    27.3 1563.29
    35.8 1559.66    38.6 1557.57    41.5 1555.26    44.3 1553.93   45.83 1553.46
    47.1 1553.06    52.7    1553    58.5 1553.51    61.3 1554.46    64.1 1556.04
    66.9 1558.29    69.7 1560.24    75.4 1561.71    81.1 1562.53    86.7 1562.66
    90.7 1562.58
#Mann= 3 ,-1,0
       0      .1       0   45.83    .045       0    58.5      .1       0
Bank Sta=45.83,58.5
XS Rating Curve= 0 ,0
Exp/Cntr(USF)=0,0
Exp/Cntr=0.3,0.1

Type RM Length L Ch R = 1 ,1274    ,317.9,314,314.3
XS GIS Cut Line= 3
 2209906.4082414715250.7675241892209925.32600306715321.503502549
2209994.41695866715386.481901274
#Sta/Elev= 30
       0 1581.81    19.1 1574.68    35.6 1568.11    43.9 1564.48      48 1562.92
    52.2 1561.51    60.5 1558.05    64.6 1556.45    68.7 1555.06    73.2 1554.08
    78.6 1553.71    84.4 1553.56    89.2 1553.88   101.9 1555.18   104.6 1555.13
   107.8 1554.61   110.1 1553.85   113.6 1552.49   117.5 1551.43  120.021550.932
   125.3 1550.71   131.6 1550.92   134.4 1551.18   137.3 1551.63   142.9 1553.43
   151.4 1557.05   154.5  1558.1   159.9 1559.28   162.7 1559.54   168.1 1559.73
#Mann= 3 ,-1,0
       0      .1       0  120.02    .045       0   131.6      .1       0
Bank Sta=120.02,131.6
XS Rating Curve= 0 ,0
Exp/Cntr(USF)=0,0
Exp/Cntr=0.3,0.1

Type RM Length L Ch R = 1 ,960     ,173.5,167.6,167.6
XS GIS Cut Line= 2
2209689.12307561715302.677131047  2209923.102176715665.343721215
#Sta/Elev= 30
       0 1586.56     7.7 1584.46    12.5  1582.7    26.8 1576.97    30.1 1575.02
    31.5 1573.97      33 1572.23    35.8 1567.71    41.6 1555.01    44.5  1551.7
    45.8 1550.42    49.9 1548.89    55.3 1547.68   57.381547.601    79.2 1547.32
   83.351547.606    93.4 1549.67   102.9 1550.56   131.5 1550.69   183.4 1551.84
   234.4 1556.23     250 1556.97   269.6  1556.2   293.3 1557.59   325.2 1557.75
   339.7 1558.64     360 1560.69   402.8 1566.56   426.5 1569.05   431.6 1570.22
#Mann= 6 ,-1,0
       0      .1       0   57.38    .045       0   83.35      .1       0
     250     .06       0     360     .07       0     370      .1       0
Bank Sta=57.38,83.35
XS Rating Curve= 0 ,0
Exp/Cntr(USF)=0,0
Exp/Cntr=0.3,0.1

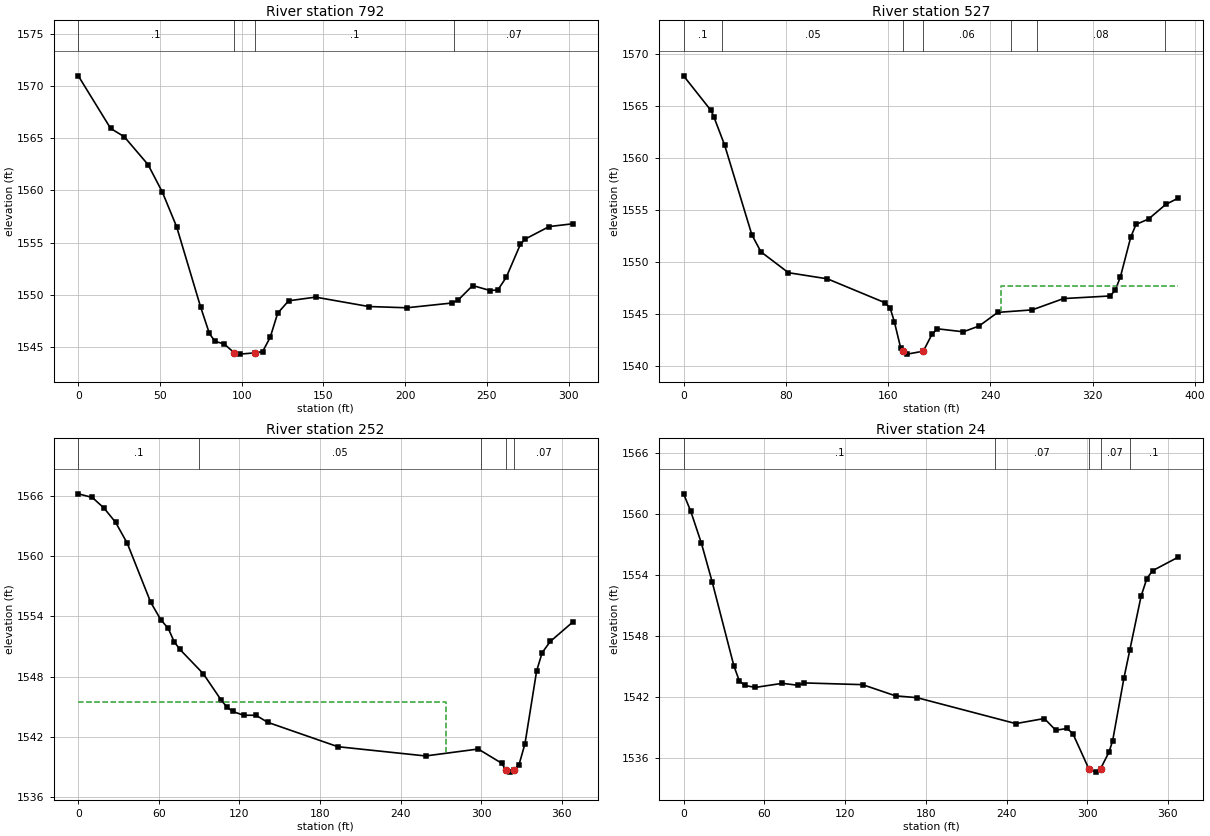
Type RM Length L Ch R = 1 ,792     ,273.1,265.1,251.8
XS GIS Cut Line= 2
2209598.78898668 715416.092310822209752.59861404715676.828417099
#Sta/Elev= 30
       0 1570.98    19.8 1565.94    28.1 1565.15    42.7 1562.47    51.5 1559.82
    60.2 1556.51    74.8 1548.86    80.2  1546.3    83.6 1545.55    89.3 1545.29
    95.3 1544.46    98.8 1544.32   108.1 1544.44   112.8 1544.57   117.4 1545.92
     122 1548.24   128.7 1549.43   145.2 1549.78   177.7 1548.88     201 1548.76
   228.8 1549.22   232.6 1549.53   241.3 1550.89     252 1550.41   256.7 1550.47
   261.8 1551.67   270.5 1554.84   273.5 1555.35   288.1 1556.54   302.7 1556.81
#Mann= 4 ,-1,0
       0      .1       0    95.3    .045       0   108.1      .1       0
     230     .07       0
Bank Sta=95.3,108.1
XS Rating Curve= 0 ,0
Exp/Cntr(USF)=0,0
Exp/Cntr=0.3,0.1

Type RM Length L Ch R = 1 ,527     ,266.4,275.2,283.4
XS GIS Cut Line= 3
 2209376.1313586715586.4962086242209412.23611037715675.629814558
2209696.56103056715736.556583171
#Sta/Elev= 30
       0 1567.93    21.4  1564.6    23.6 1564.01    32.1 1561.26    53.4 1552.62
    60.5 1550.98      82 1548.97   112.5 1548.38   157.5 1546.08   161.6 1545.54
   164.8 1544.26   169.7 1541.76  171.681541.435   174.9 1541.13  187.461541.414
   194.3 1543.05   198.4 1543.57   218.8 1543.28   231.1 1543.84   245.7 1545.15
   272.6 1545.39   297.1 1546.48   333.4 1546.73   337.5 1547.27   341.6 1548.57
   349.7  1552.4   353.8 1553.62   363.6 1554.14     377 1555.54   386.9 1556.16
#Mann= 7 ,-1,0
       0      .1       0      30     .05       0  171.68    .045       0
  187.46     .06       0  256.17     .05       0  276.17     .08       0
  376.17     .07       0
#XS Ineff= 2 , 0
                          247.88         1547.72
Permanent Ineff=
       F       F
Bank Sta=171.68,187.46
XS Rating Curve= 0 ,0
Exp/Cntr(USF)=0,0
Exp/Cntr=0.3,0.1

Type RM Length L Ch R = 1 ,252     ,227.4,227.4,227.4
XS GIS Cut Line= 2
2209259.91918884715631.6271483382209405.46646941715970.109196187
#Sta/Elev= 30
       0  1566.2    10.4 1565.84    19.1 1564.79    27.8 1563.36    36.5 1561.27
    53.9 1555.41    61.4 1553.68      67  1552.8    71.4 1551.48    75.7 1550.71
    93.1 1548.29   106.2 1545.71   110.5    1545   114.9 1544.54   123.2 1544.16
   132.3 1544.16     141 1543.46   193.3 1541.03   258.6 1540.11   297.8  1540.8
   315.2 1539.39  318.361538.712   321.1  1538.5  324.461538.695   328.2 1539.25
   332.6 1541.32   341.3 1548.58   345.4 1550.39   351.5 1551.51   368.4 1553.46
#Mann= 5 ,-1,0
       0      .1       0      90     .05       0     300     .07       0
  318.36    .045       0  324.46     .07       0
#XS Ineff= 2 , 0
          273.71 1545.44
Permanent Ineff=
       F       F
Bank Sta=318.36,324.46
XS Rating Curve= 0 ,0
Exp/Cntr(USF)=0,0
Exp/Cntr=0.3,0.1

Type RM Length L Ch R = 1 ,24      ,,,
XS GIS Cut Line= 3
2209133.66538499715683.8662110562209143.81984642715905.233470349
2209191.54581517716043.334145872
#Sta/Elev= 30
       0 1561.94     5.3 1560.24    13.3 1557.06    21.3 1553.26    37.4 1545.02
    41.4 1543.56    45.4  1543.1    53.4 1542.91    73.4 1543.31    85.4 1543.11
    89.4 1543.35     133 1543.18   157.5 1542.08   173.5  1541.9   246.9 1539.35
   268.1 1539.85   276.6  1538.7     285 1538.87   289.3 1538.37  301.151534.911
   306.2 1534.58   309.9 1534.91   316.2 1536.56   318.9 1537.68   327.3 1543.85
   331.6 1546.56     340 1551.87   344.3 1553.61   348.5 1554.38   367.7 1555.72
#Mann= 5 ,-1,0
       0      .1       0   231.6     .07       0  301.15    .045       0
   309.9     .07       0   331.6      .1       0
Bank Sta=301.15,309.9
XS Rating Curve= 0 ,0
Exp/Cntr(USF)=0,0
Exp/Cntr=0.3,0.1
LCMann Table=0

Chan Stop Cuts=-1
Use User Specified Reach Order=0
Composite Channel Slope=5